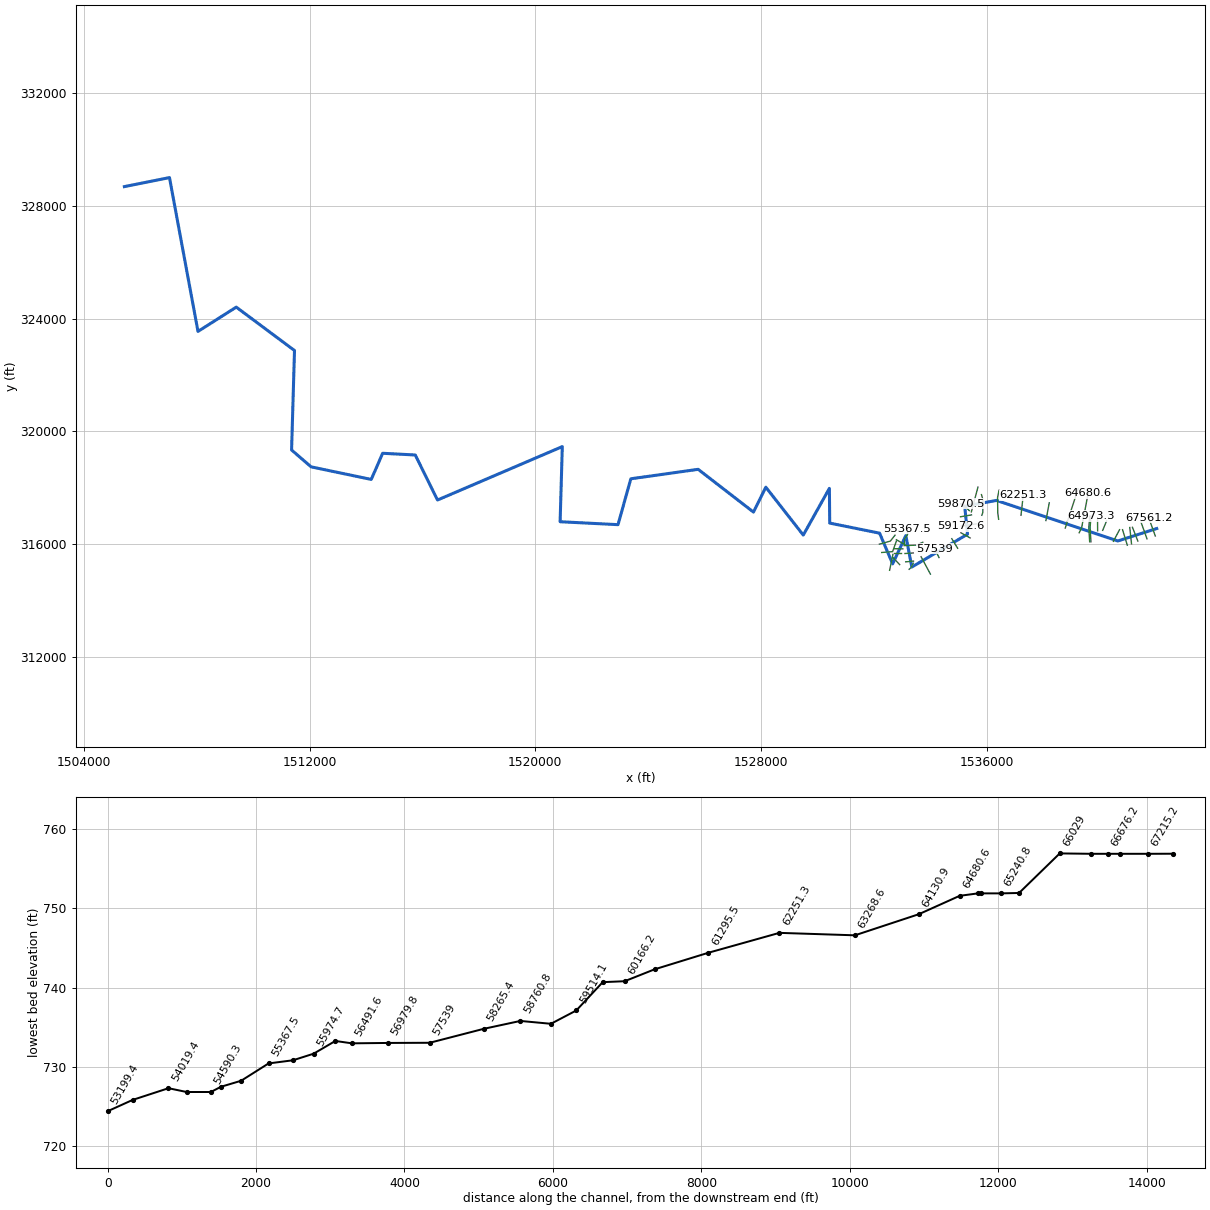
--- McKimCr.prj (project) ---

Proj Title=McKimCr
Current Plan=p01
Default Exp/Contr=0,0
English Units
Geom File=g01
Flow File=f01
Plan File=p01
BEGIN DESCRIPTION:
AMEC Environment & Infrastructure, 2013
Projection: NAD 1983 State Plane West Virginia North FIPS 4701 (US Feet)
Vertical Datum: NAVD 1988
END DESCRIPTION:
DSS Export Rating Curves= 0
DSS Export Rating Curve Sorted= 0
DSS Export Volume Flow Curves= 0
DXF OffsetX= 0
DXF OffsetY= 0
DXF ScaleX= 0
DXF ScaleY= 0

--- McKimCr.p01 (plan) ---

Plan Title=Floodplain
Program Version=4.00
Geom File=g01
Flow File=f01
K Sum by GR=0
Std Step Tol=0.01
Critical Tol=0.01
Num of Std Step Trials=20
Max Error Tol=0.3
Flow Tol Ratio=0.001
Split Flow NTrial=30
Split Flow Tol=0.02
Split Flow Ratio=0.02
Log Output Level=0
Friction Slope Method=1
Unsteady Friction Slope Method=2
Unsteady Bridges Friction Slope Method=1
Global Log Level=0
CheckData=False
Run HTab=0
Run UNet=0
Run PostProcess=0
UNET Theta=0
UNET Theta Warmup=0
UNET ZTol=0
UNET ZSATol=0
UNET MxIter=0
UNET MaxInSteps=0
UNET DtIC=0
UNET DtMin=0
UNET MaxCRTS=0
UNET WFStab=0
UNET SFStab=0
UNET WFX=0
UNET SFX=0
UNET DSS MLevel=0
UNET DZMax Abort=0
UNET Convert EG Bridges=0
UNET Use Existing IB Tables=0
UNET Froude Limit=0
UNET Froude Power=0
Write IC File=0
Echo Input=False
Echo Output=False
Write Detailed=0

--- McKimCr.f01 (steady flow) ---

Flow Title=USGS Regress. Eqn. (2010) - Western-Plateaus
Program Version=4.10
Number of Profiles= 1
Profile Names=P100yr
River Rch & RM=McKimCr,Main            ,67561.2
    3054
River Rch & RM=McKimCr,Main            ,64130.9
    3166
River Rch & RM=McKimCr,Main            ,63268.6
    3325
River Rch & RM=McKimCr,Main            ,57539
    3490
River Rch & RM=McKimCr,Main            ,56979.8
    3507
River Rch & RM=McKimCr,Main            ,53536.1
    3529
River Rch & RM=McKimCr,Main            ,44048
    3764
River Rch & RM=McKimCr,Main            ,40135.7
    3790
River Rch & RM=McKimCr,Main            ,39848.7
    4060
River Rch & RM=McKimCr,Main            ,34990.5
    4178
River Rch & RM=McKimCr,Main            ,33065.9
    4201
River Rch & RM=McKimCr,Main            ,32639.5
    4820
River Rch & RM=McKimCr,Main            ,29047.6
    4837
River Rch & RM=McKimCr,Main            ,25285.4
    4959
River Rch & RM=McKimCr,Main            ,24123.2
    4966
River Rch & RM=McKimCr,Main            ,23376.5
    5396
River Rch & RM=McKimCr,Main            ,20077
    5456
River Rch & RM=McKimCr,Main            ,14668.7
    5752
River Rch & RM=McKimCr,Main            ,11533.8
    5785
River Rch & RM=McKimCr,Main            ,9374.6
    6216
Boundary for River Rch & Prof#=McKimCr,Main            , 1
Up Type= 0
Dn Type= 3
Dn Slope=0.0033
DSS Import GetInterval= 0
DSS Import GetPeak= 0
DSS Import FillOption= 0

--- McKimCr.g01 (geometry) ---

Geom Title=USGS 3m DEM
Program Version=4.10

River Reach=McKimCr         ,Main
Reach XY= 30
     1542027.434      316557.503      1540647.77      316117.002
     1536347.423      317553.634     1535220.687      317348.773
     1535321.381      316357.454     1533345.687      315192.523
     1533133.881      316307.106     1532666.867       315305.37
     1532203.326      316393.912     1530435.965      316749.815
     1530423.812      317980.717     1529498.465      316326.204
      1528170.34       318024.12      1527732.84       317140.44
      1525772.77      318656.065     1523385.617      318320.995
     1522931.519      316694.917     1520879.205      316798.878
     1520956.521      319461.301      1516532.91       317568.94
     1515744.716      319164.426     1514588.466       319225.19
     1514183.952      318298.107     1512052.008      318744.287
     1511360.106      319342.089     1511463.466      322867.551
     1509399.464      324405.748     1508042.398      323545.214
     1507031.843      328997.762     1505432.323       328677.85

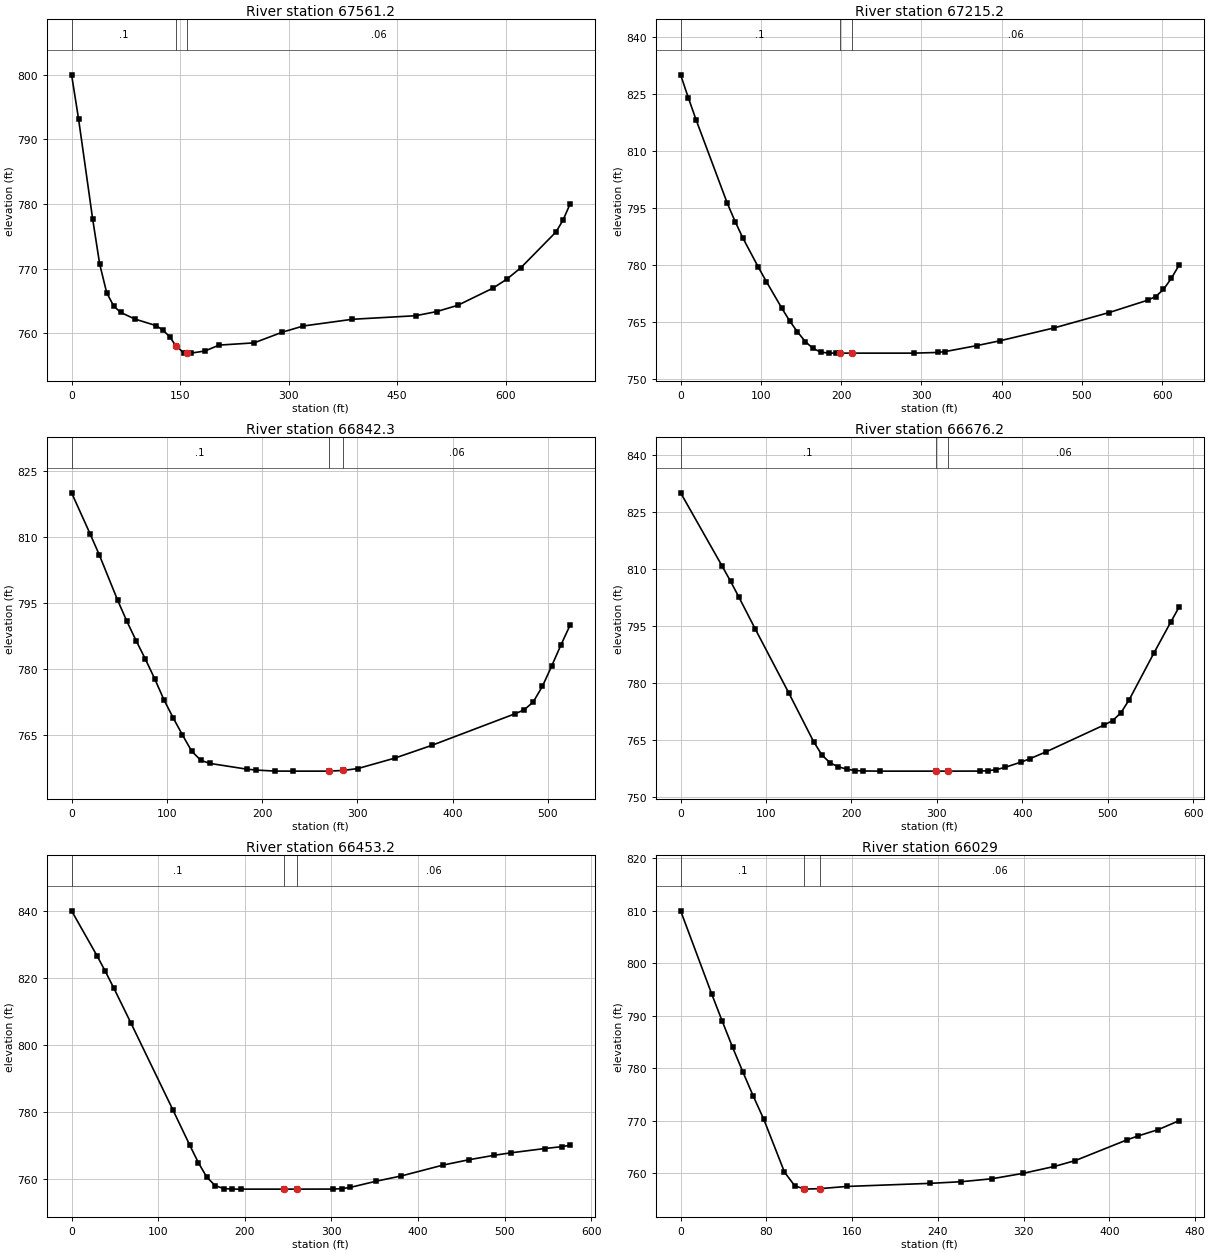
Type RM Length L Ch R = 1 ,67561.2 ,343.4,346,348.6
XS GIS Cut Line= 2
     1541976.699      316293.188     1541743.908       316941.74
#Sta/Elev= 30
       0  799.99     9.7  793.12    29.1  777.69    38.8  770.72    48.5  766.26
    58.2   764.2    67.9  763.21    87.4  762.19   116.5  761.18   126.2  760.49
   135.9   759.4     144  758.06   155.3  756.93     159  756.92     165  756.91
   184.4  757.24   203.8  758.15   252.3   758.5   291.2  760.15   320.3  761.11
   388.2  762.15   475.6   762.7   504.7  763.34   533.8  764.31   582.3  766.96
   601.7  768.36   621.1  770.13   669.6  775.66   679.4   777.5   689.1     780
#Mann= 3 , 0 , 0
       0      .1       0     144    .045       0     159     .06       0
Bank Sta=144,159
XS Rating Curve= 0 ,0
Exp/Cntr=0.3,0.1

Type RM Length L Ch R = 1 ,67215.2 ,375.2,372.9,370.7
XS GIS Cut Line= 2
     1541682.476      316192.918      1541472.65      316777.551
#Sta/Elev= 30
       0     830     9.7   823.9    19.4   818.1    58.2  796.24    67.9  791.47
    77.6  787.12      97  779.41   106.8  775.71   126.2  768.67   135.9  765.35
   145.6  762.48   155.3  759.95     165  758.12   174.7  757.17   184.4  756.91
   194.1   756.9   198.3   756.9   213.3   756.9   291.2   756.9   320.3  757.08
     330  757.32   368.8  758.86   397.9  760.14   465.9  763.55   533.8  767.55
   582.3  770.82     592  771.77   601.7  773.62   611.4  776.51   621.2  780.01
#Mann= 3 , 0 , 0
       0      .1       0   198.3    .045       0   213.3     .06       0
Bank Sta=198.3,213.3
XS Rating Curve= 0 ,0
Exp/Cntr=0.3,0.1

Type RM Length L Ch R = 1 ,66842.3 ,172,166,159.7
XS GIS Cut Line= 2
     1541357.674      316113.395     1541167.184      316600.734
#Sta/Elev= 30
       0     820    19.4  810.71    29.1  805.92    48.4  795.61    58.1  790.84
    67.8  786.45    77.5  782.27    87.2  777.85    96.9  773.09   106.6  768.99
   116.3  765.13     126  761.44   135.7  759.33   145.4  758.64   184.1  757.34
   193.8  757.14   213.2  756.91   232.6   756.9   269.8   756.9   284.8  757.05
   300.4  757.48   339.1  759.84   377.9  762.73   465.1  769.88   474.8  770.76
   484.5  772.57   494.2  776.14   503.9  780.74   513.6   785.5   523.2     790
#Mann= 3 , 0 , 0
       0      .1       0   269.8    .045       0   284.8     .06       0
Bank Sta=269.8,284.8
XS Rating Curve= 0 ,0
Exp/Cntr=0.3,0.1

Type RM Length L Ch R = 1 ,66676.2 ,218.6,223,227.4
XS GIS Cut Line= 2
     1541134.033      316013.808     1541072.241      316594.146
#Sta/Elev= 30
       0     830    48.6  810.75    58.4  806.79    68.1  802.65    87.5  794.17
   126.4  777.53   155.6  764.68   165.4  761.15   175.1  759.05   184.8  758.03
   194.5  757.41   204.3  757.06     214  756.94   233.4   756.9   298.4   756.9
   313.4   756.9   350.2  756.91   359.9     757   369.6   757.3   379.4  757.86
   398.8  759.29   408.5  760.12     428  761.98   496.1  769.05   505.8  770.17
   515.5  772.23   525.3  775.71   554.4  788.05   573.9  796.09   583.6     800
#Mann= 3 , 0 , 0
       0      .1       0   298.4    .045       0   313.4     .06       0
Bank Sta=298.4,313.4
XS Rating Curve= 0 ,0
Exp/Cntr=0.3,0.1

Type RM Length L Ch R = 1 ,66453.2 ,442.3,424.2,406.1
XS GIS Cut Line= 2
     1540984.699      315966.292     1540816.336      316516.694
#Sta/Elev= 27
       0     840    29.3  826.62      39   821.9    48.8  816.91    68.3  806.61
   117.1   780.5   136.6  769.95   146.3  764.84   156.1  760.48   165.8  757.94
   175.6  757.07   185.4  756.91   195.1   756.9   245.7   756.9   260.7   756.9
   302.4  756.92   312.2  757.05   321.9  757.42   351.2  759.24   380.5  760.82
   429.2   764.1   458.5  765.66   487.8     767   507.3  767.74   546.3  769.02
   565.8  769.57   575.6     770
#Mann= 3 , 0 , 0
       0      .1       0   245.7    .045       0   260.7     .06       0
Bank Sta=245.7,260.7
XS Rating Curve= 0 ,0
Exp/Cntr=0.3,0.1

Type RM Length L Ch R = 1 ,66029   ,546.3,548,549.7
XS GIS Cut Line= 2
     1540492.257      316105.849     1540709.443      316517.138
#Sta/Elev= 23
       0     810    29.1  794.09    38.8  788.97    48.4  784.02    58.1  779.27
    67.8  774.67    77.5   770.3    96.9  760.19   106.6  757.55   115.2  757.02
   116.3  756.95   130.2  757.05     155  757.46   232.6  758.05   261.6  758.36
   290.7  758.93   319.8  759.97   348.8  761.28   368.2  762.39   416.7  766.36
   426.4  767.06   445.7   768.3   465.1     770
#Mann= 3 , 0 , 0
       0      .1       0   115.2    .045       0   130.2     .06       0
Bank Sta=115.2,130.2
XS Rating Curve= 0 ,0
Exp/Cntr=0.3,0.1

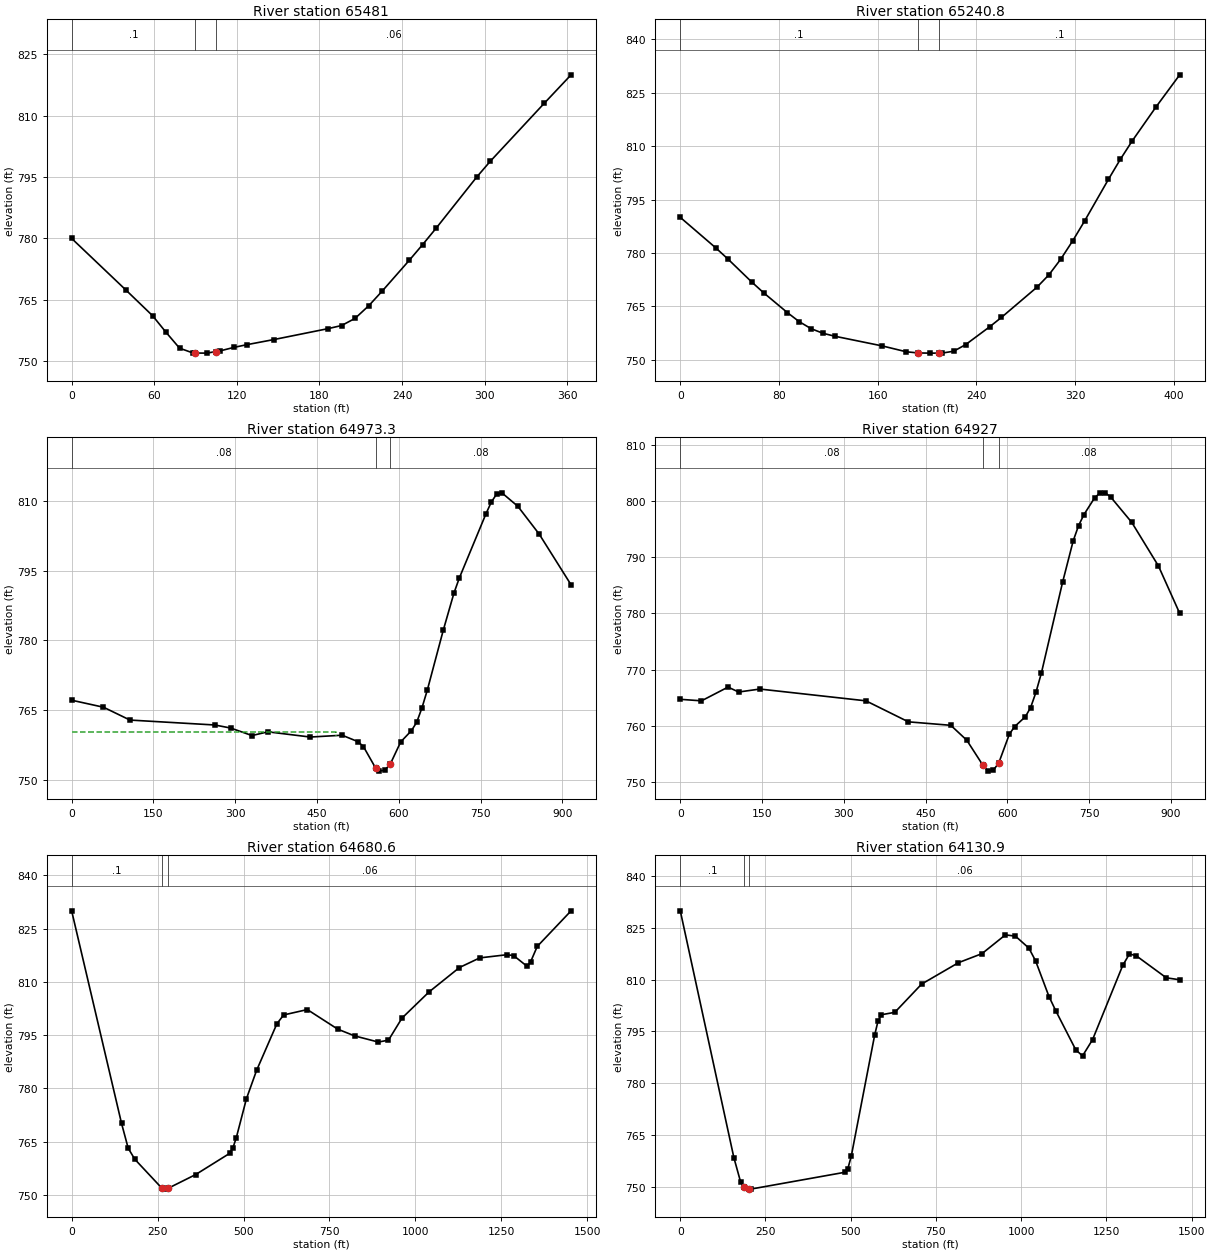
Type RM Length L Ch R = 1 ,65481   ,231.1,240.1,249.1
XS GIS Cut Line= 2
     1540112.246      316493.556     1540250.767      316828.925
#Sta/Elev= 25
       0     780    39.2  767.45    58.8   761.1    68.6  757.03    78.4  753.16
    88.3  751.97    89.8  751.97    98.1  751.95   104.8  752.33   107.9   752.5
   117.7  753.34   127.5  754.03   147.1  755.28   186.3  757.94   196.1   758.7
   205.9  760.45   215.8  763.53   225.6  767.12   245.2  774.62     255   778.5
   264.8  782.51   294.2  794.98     304  798.82   343.2     813   362.8     820
#Mann= 3 , 0 , 0
       0      .1       0    89.8    .045       0   104.8     .06       0
Bank Sta=89.8,104.8
XS Rating Curve= 0 ,0
Exp/Cntr=0.3,0.1

Type RM Length L Ch R = 1 ,65240.8 ,269.5,267.5,265.5
XS GIS Cut Line= 2
      1539932.27      316477.383     1539930.122      316882.294
#Sta/Elev= 30
       0     790    28.9   781.4    38.6  778.32    57.8   771.9    67.5  768.86
    86.8  763.28    96.4  760.74     106  758.77   115.7  757.47   125.3  756.64
   163.9  753.91   183.2  752.28   192.8  751.95   202.5   751.9   209.7   751.9
   212.1   751.9   221.7  752.44   231.4   754.3   250.7  759.26   260.3   761.9
   289.2  770.41   298.9  773.89   308.5  778.29   318.2  783.44   327.8  788.99
   347.1  800.66   356.7  806.25   366.4  811.46   385.6  820.95   404.9     830
#Mann= 3 , 0 , 0
       0      .1       0   192.8    .045       0   209.7      .1       0
Bank Sta=192.8,209.7
XS Rating Curve= 0 ,0
Exp/Cntr=0.3,0.1

Type RM Length L Ch R = 1 ,64973.3 ,46.3,46.4,46.3
XS GIS Cut Line= 3
     1539696.267      316087.098     1539665.813      316592.017
     1539698.409      317000.814
#Sta/Elev= 30
       0  767.15    58.4  765.64     107  762.88   262.6  761.82   291.8  761.16
   330.7  759.55   359.9  760.35   437.7  759.23   496.1  759.62   525.4  758.22
   535.1  757.18   557.5  752.55   564.4   751.9   574.2  752.12     584  753.33
   603.5  758.19     623  760.58   632.8   762.4   642.5  765.52   652.3  769.34
   681.6  782.23   701.1  790.18   710.9  793.41   759.7   807.2   769.5  809.72
   779.2  811.45     789  811.74   818.3  808.84   857.4  802.87   915.9  791.96
#Mann= 3 , 0 , 0
       0     .08       0   557.5    .045       0     584     .08       0
#XS Ineff= 2 , 0
          484.51  760.23
Permanent Ineff=
       F       F
Bank Sta=557.5,584
XS Rating Curve= 0 ,0
Exp/Cntr=0.3,0.1

Type RM Length L Ch R = 1 ,64927   ,248.8,246.4,244
XS GIS Cut Line= 3
     1539650.097      316087.079     1539619.644      316591.998
     1539652.239      317000.795
#Sta/Elev= 30
       0  764.69    38.9  764.42    87.6  766.87     107  765.99   145.9  766.52
   340.5  764.42   418.3  760.68   496.1  760.06   525.4  757.41   554.7  752.99
   564.4   751.9   574.2  752.08     584  753.34   603.5  758.48   613.2  759.84
   632.8  761.58   642.5  763.23   652.3  765.95   662.1  769.32   701.1  785.54
   720.6  792.93   730.4  795.62   740.2  797.58   759.7  800.56   769.5  801.44
   779.2  801.47     789  800.76     828   796.2   876.9  788.44   915.9     780
#Mann= 3 , 0 , 0
       0     .08       0   554.7    .045       0     584     .08       0
Bank Sta=554.7,584
XS Rating Curve= 0 ,0
Exp/Cntr=0.3,0.1

Type RM Length L Ch R = 1 ,64680.6 ,552.5,549.7,546.9
XS GIS Cut Line= 3
     1539278.407      316407.747     1539362.926      316571.005
      1539598.98      317817.722
#Sta/Elev= 30
       0     830   145.1  770.13   164.5  763.11   183.8     760   262.5  751.85
   272.4  751.59   280.6  751.82   360.9   755.7   459.2  761.64   469.1  763.21
   478.9  766.06   508.4  777.05   537.9  785.03     597  798.17   616.6  800.66
   685.5  802.18     774  796.66   823.2  794.76     892  793.03   921.6  793.56
   960.9  799.78  1039.6  807.15  1128.1  814.03  1187.1  816.74  1265.8  817.63
  1285.5   817.4  1324.8  814.36  1334.7  815.56  1354.3  819.97  1452.7     830
#Mann= 3 , 0 , 0
       0      .1       0   262.5    .045       0   280.6     .06       0
Bank Sta=262.5,280.6
XS Rating Curve= 0 ,0
Exp/Cntr=0.3,0.1

Type RM Length L Ch R = 1 ,64130.9 ,860.7,862.3,863.7
XS GIS Cut Line= 2
     1538785.287      316574.073     1539241.536      317966.334
#Sta/Elev= 30
       0     830   157.3  758.38     177  751.34   187.8  749.96   202.8  749.34
   206.5  749.27   481.8  754.14   491.6  755.22   501.5  758.78   570.3  793.99
   580.2  798.06     590  799.86   629.3  800.55     708  808.75   816.1  814.96
     885  817.58   953.8  823.03   983.3  822.65  1022.6  819.19  1042.3  815.49
  1081.6  805.14  1101.3  801.05  1160.3  789.66    1180  787.92  1209.4  792.62
    1298  814.17  1317.6  817.49  1337.3  816.98  1425.8  810.57  1465.1     810
#Mann= 3 , 0 , 0
       0      .1       0   187.8    .045       0   202.8     .06       0
Bank Sta=187.8,202.8
XS Rating Curve= 0 ,0
Exp/Cntr=0.3,0.1

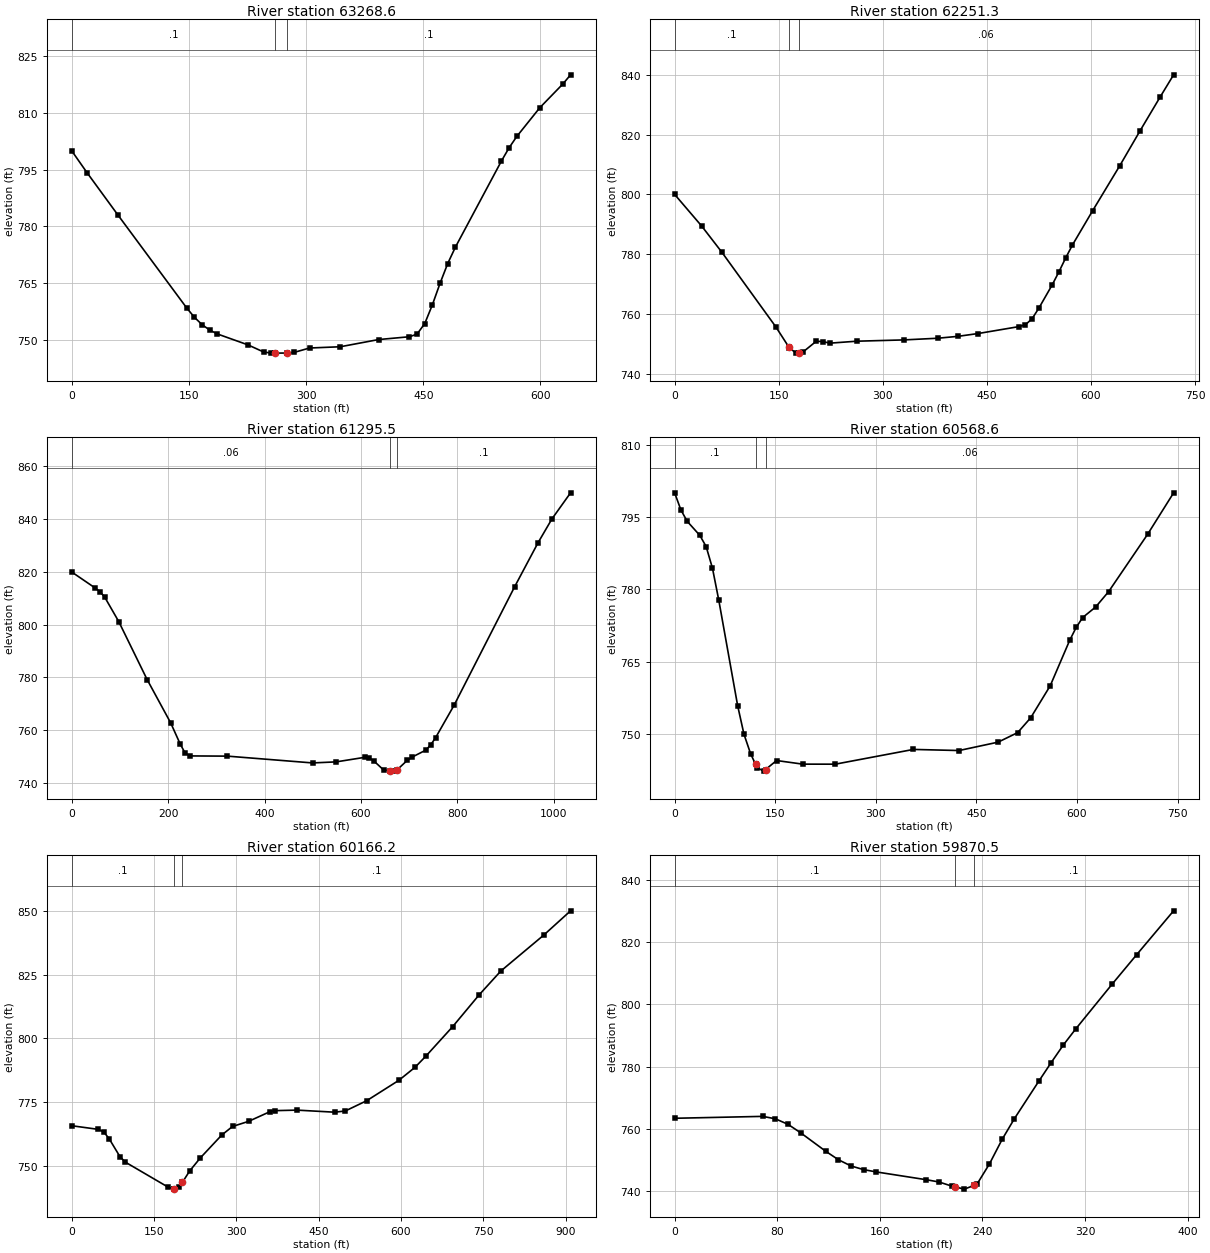
Type RM Length L Ch R = 1 ,63268.6 ,1015.3,1017.3,1019.2
XS GIS Cut Line= 2
     1538099.806      316840.591     1538217.916      317468.071
#Sta/Elev= 30
       0     800    19.6  794.23    58.9  783.13   147.4  758.48   157.2  756.04
     167   754.1   176.8  752.67   186.6  751.65   225.9  748.76   245.6  746.91
   255.4   746.6   260.8   746.6   275.8  746.63   284.9   746.8   304.5  747.95
   343.8  748.28   392.9  750.18   432.2  750.92     442   751.6   451.9  754.39
   461.7  759.36   471.5  765.03   481.3  770.23   491.2  774.58   550.1   797.3
   559.9  800.78   569.7  803.75   599.2  811.34   628.7   817.6   638.5     820
#Mann= 3 , 0 , 0
       0      .1       0   260.8    .045       0   275.8      .1       0
Bank Sta=260.8,275.8
XS Rating Curve= 0 ,0
Exp/Cntr=0.3,0.1

Type RM Length L Ch R = 1 ,62251.3 ,952.9,955.7,958.5
XS GIS Cut Line= 2
     1537216.052      317028.251      1537296.51      317742.773
#Sta/Elev= 30
       0     800    38.9  789.43      68  780.68   145.8   755.7   164.2  749.07
   165.2  748.72   174.9  746.91   179.2  747.05   184.6  747.22     204  750.87
   213.8  750.78   223.5  750.24   262.4   750.9   330.4  751.33     379  751.89
   408.1  752.52   437.2  753.46   495.6  755.76   505.3  756.38     515  758.39
   524.7   761.9   544.1  769.76   553.8  774.12   563.6   778.8   573.3  783.11
   602.4  794.57   641.3  809.54   670.4  821.17   699.6  832.58     719     840
#Mann= 3 , 0 , 0
       0      .1       0   164.2    .045       0   179.2     .06       0
Bank Sta=164.2,179.2
XS Rating Curve= 0 ,0
Exp/Cntr=0.3,0.1

Type RM Length L Ch R = 1 ,61295.5 ,726.9,726.9,726.9
XS GIS Cut Line= 4
     1536423.385      316885.881     1536393.679      317108.878
     1536384.899      317648.088     1536436.424      317913.334
#Sta/Elev= 30
       0  819.99    48.9  813.88    58.7  812.49    68.5  810.46    97.8  801.12
   156.5  779.16   205.4   762.7     225  754.73   234.8  751.42   244.6  750.17
     323  750.09   499.5  747.51   548.5  747.91   607.4  749.63   617.2  749.38
     627  748.19   646.6  744.87   659.8  744.43   666.2   744.4   674.8  744.89
   695.6  748.45   705.4  749.68   734.8  752.41   744.6  754.42   754.4  757.03
   793.2  769.49   918.6  814.41   966.9  831.04   995.8   840.1  1034.4     850
#Mann= 3 , 0 , 0
       0     .06       0   659.8    .045       0   674.8      .1       0
Bank Sta=659.8,674.8
XS Rating Curve= 0 ,0
Exp/Cntr=0.3,0.1

Type RM Length L Ch R = 1 ,60568.6 ,408.2,402.4,396.5
XS GIS Cut Line= 4
     1535827.837      317028.674     1535862.824      317126.013
     1535865.559      317582.677     1535815.325      317759.688
#Sta/Elev= 30
       0  800.01     9.4  796.44    18.8  794.09    37.6  791.18      47  788.86
    56.4  784.38    65.8  777.77      94  755.85   103.4  749.95   113.2  745.94
   120.6  743.73   122.9  743.04   132.6   742.3   135.6  742.63     152   744.5
   190.9  743.75   239.5  743.74   356.1   746.8   424.1  746.57   482.4  748.31
   511.5  750.28     531  753.36   560.1     760   589.2  769.44   598.8  772.09
   608.5  774.15   627.9  776.34   647.3  779.54   705.4  791.42   744.1     800
#Mann= 3 , 0 , 0
       0      .1       0   120.6    .045       0   135.6     .06       0
Bank Sta=120.6,135.6
XS Rating Curve= 0 ,0
Exp/Cntr=0.3,0.1

Type RM Length L Ch R = 1 ,60166.2 ,271.5,295.8,320.1
XS GIS Cut Line= 2
     1535457.202      317147.915     1535690.239      318026.259
#Sta/Elev= 30
       0  765.68    48.9  764.24    58.6  763.22    68.4  760.57    87.9  753.59
    97.7  751.41   175.9  741.56   185.7   740.8   186.9  740.91   195.4  741.66
   201.9   743.5     215  747.93   234.5  753.07   273.6  762.06   293.1  765.39
   322.4   767.4   361.5  771.22   371.3   771.6   410.4   771.8   478.8  770.99
   498.3  771.45   537.4  775.49     596  783.49   625.4   788.6   644.9  792.91
   693.8  804.51   742.6  817.13   781.7  826.38   859.9  840.48   908.7     850
#Mann= 3 , 0 , 0
       0      .1       0   186.9    .045       0   201.9      .1       0
Bank Sta=186.9,201.9
XS Rating Curve= 0 ,0
Exp/Cntr=0.3,0.1

Type RM Length L Ch R = 1 ,59870.5 ,334.9,356.4,377.8
XS GIS Cut Line= 3
     1535384.285      317192.185     1535200.405      317369.365
     1535081.463      317430.561
#Sta/Elev= 27
       0  763.42    68.8  764.03    78.6  763.24    88.4  761.48    98.2  758.78
   117.8  752.84   127.7  750.12   137.5  748.12   147.3  746.95   157.1  746.21
   196.4  743.69   206.2  742.97   216.1  741.65   218.7  741.39   225.9  740.68
   233.7   741.9   235.7  742.21   245.5  748.77   255.4  756.65   264.9  763.26
     284  775.33   293.6  781.27   303.1  786.93   312.7  792.05   341.3  806.53
   360.4  815.97   389.1     830
#Mann= 3 , 0 , 0
       0      .1       0   218.7    .045       0   233.7      .1       0
Bank Sta=218.7,233.7
XS Rating Curve= 0 ,0
Exp/Cntr=0.3,0.1

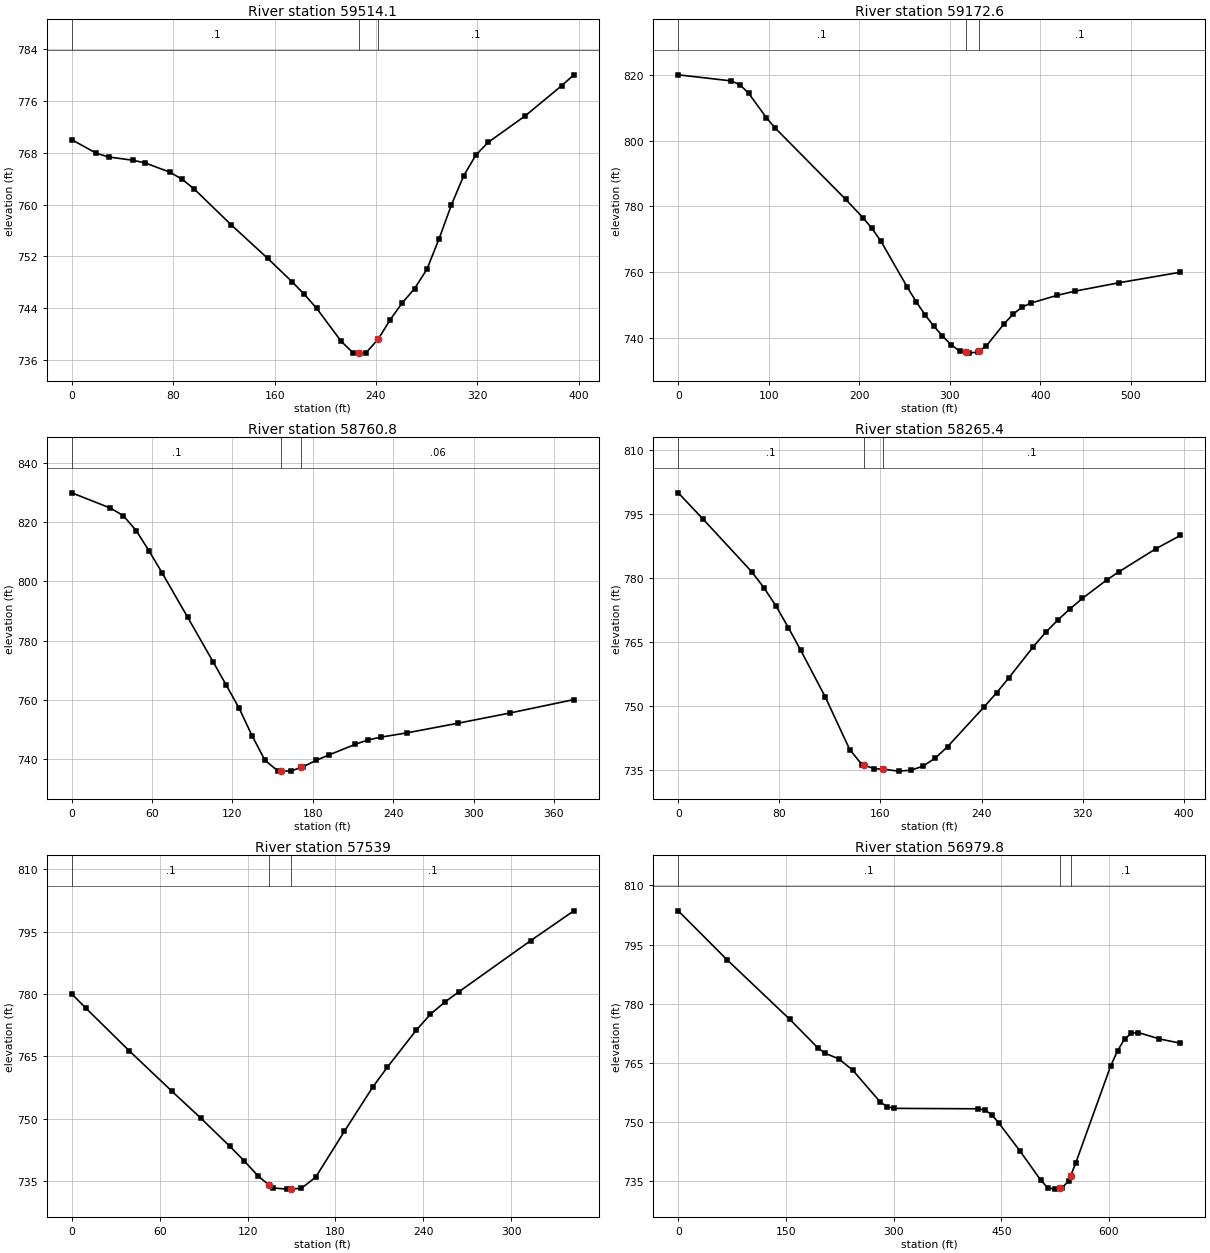
Type RM Length L Ch R = 1 ,59514.1 ,342.1,341.5,340.9
XS GIS Cut Line= 2
     1535462.016      317040.815     1535071.505      316974.456
#Sta/Elev= 30
       0     770    19.3  767.92      29  767.34    48.3  766.83      58  766.41
    77.3     765      87  763.91    96.6   762.4   125.6  756.91   154.6   751.7
   173.9  748.08   183.6  746.14   193.2     744   212.6  738.91   222.2   737.1
   226.8   737.1   231.9   737.1   241.8  739.27   251.2  742.25   260.8  744.86
   270.5  747.06   280.2  750.04   289.8  754.73   299.5  759.95   309.2  764.44
   318.8  767.63   328.5  769.59   357.5  773.64   386.4  778.31   396.1     780
#Mann= 3 , 0 , 0
       0      .1       0   226.8    .045       0   241.8      .1       0
Bank Sta=226.8,241.8
XS Rating Curve= 0 ,0
Exp/Cntr=0.3,0.1

Type RM Length L Ch R = 1 ,59172.6 ,426.8,411.7,397.2
XS GIS Cut Line= 2
     1535649.024      316724.609      1535100.35      316643.958
#Sta/Elev= 30
       0     820    58.4  818.16    68.1     817    77.8  814.39    97.3  806.99
     107  803.85   184.9  782.17   204.3  776.51     214  773.32   223.8  769.48
     253  755.47   262.7  751.11   272.4  747.15   282.2  743.66   291.9  740.64
   301.6  737.91   311.3  735.97   317.6  735.62   321.1  735.42   330.8  735.75
   332.6  736.11   340.5  737.67     360  744.35   369.7   747.2   379.4  749.33
   389.2   750.6   418.4  752.97   437.8  754.23   486.5  756.79   554.6     760
#Mann= 3 , 0 , 0
       0      .1       0   317.6    .045       0   332.6      .1       0
Bank Sta=317.6,332.6
XS Rating Curve= 0 ,0
Exp/Cntr=0.3,0.1

Type RM Length L Ch R = 1 ,58760.8 ,506.8,495.4,483.5
XS GIS Cut Line= 2
     1535412.804      316224.677     1535085.747      316407.991
#Sta/Elev= 26
       0     830    28.8  824.85    38.4  822.29    48.1  817.23    57.7  810.34
    67.3  803.02    86.5   787.9   105.8  772.58   115.4  764.86     125  757.04
   134.6   747.8   144.2  739.49   153.8  735.87   156.5  735.84   163.4  735.78
   171.5  737.08     173  737.32   182.7  739.47   192.3   741.3   211.5  744.82
   221.1  746.33   230.7  747.28     250  748.71   288.4     752   326.9  755.43
   374.9     760
#Mann= 3 , 0 , 0
       0      .1       0   156.5    .045       0   171.5     .06       0
Bank Sta=156.5,171.5
XS Rating Curve= 0 ,0
Exp/Cntr=0.3,0.1

Type RM Length L Ch R = 1 ,58265.4 ,728.5,726.4,724.3
XS GIS Cut Line= 2
     1534970.821      315859.065     1534763.199      316197.772
#Sta/Elev= 30
       0     800    19.4  793.92    58.1  781.52    67.8  777.77    77.5  773.42
    87.2  768.38    96.9  763.12   116.3  752.19   135.7  739.84   145.4   736.3
   146.7  736.18     155  735.39   161.7  735.24   174.4  734.78   184.1  734.99
   193.8  735.96   203.5  737.86   213.2  740.53   242.2  749.89   251.9  753.13
   261.6  756.64     281  763.95   290.7  767.28   300.4   770.2   310.1  772.83
   319.8  775.25   339.1  779.59   348.8  781.51   377.9  786.89   397.3     790
#Mann= 3 , 0 , 0
       0      .1       0   146.7    .045       0   161.7      .1       0
Bank Sta=146.7,161.7
XS Rating Curve= 0 ,0
Exp/Cntr=0.3,0.1

Type RM Length L Ch R = 1 ,57539   ,558.3,559.2,560
XS GIS Cut Line= 2
     1534310.444      315529.092     1534156.883       315835.46
#Sta/Elev= 23
       0     780     9.8  776.52    39.2  766.32    68.5  756.53    88.1   750.1
   107.7  743.38   117.5  739.89   127.3  736.13   134.9  733.94   137.1  733.31
   146.9  733.02   149.9  733.08   156.7  733.22   166.4  735.86     186  746.89
   205.6  757.66   215.4  762.36     235  771.22   244.8   775.1   254.6  778.03
   264.4  780.56   313.3  792.84   342.7     800
#Mann= 3 , 0 , 0
       0      .1       0   134.9    .045       0   149.9      .1       0
Bank Sta=134.9,149.9
XS Rating Curve= 0 ,0
Exp/Cntr=0.3,0.1

Type RM Length L Ch R = 1 ,56979.8 ,510.1,488.2,466.3
XS GIS Cut Line= 2
      1534005.55       314941.71       1533674.6      315557.866
#Sta/Elev= 30
       0  803.57      68  791.16   155.4  776.05   194.3  768.86     204  767.49
   223.4  766.05   242.8  763.22   281.7  755.02   291.4  753.89   301.1  753.48
   417.7  753.37   427.4  753.03   437.1   751.8   446.8  749.71     476  742.69
   505.1  735.24   514.8  733.33   524.6     733   531.5  733.17   534.3  733.24
     544  735.14   546.5  736.29   553.7  739.62   602.3   764.2     612  768.08
   621.7  771.07   631.4  772.53   641.1  772.69   670.3  771.09   699.4     770
#Mann= 3 , 0 , 0
       0      .1       0   531.5    .045       0   546.5      .1       0
Bank Sta=531.5,546.5
XS Rating Curve= 0 ,0
Exp/Cntr=0.3,0.1

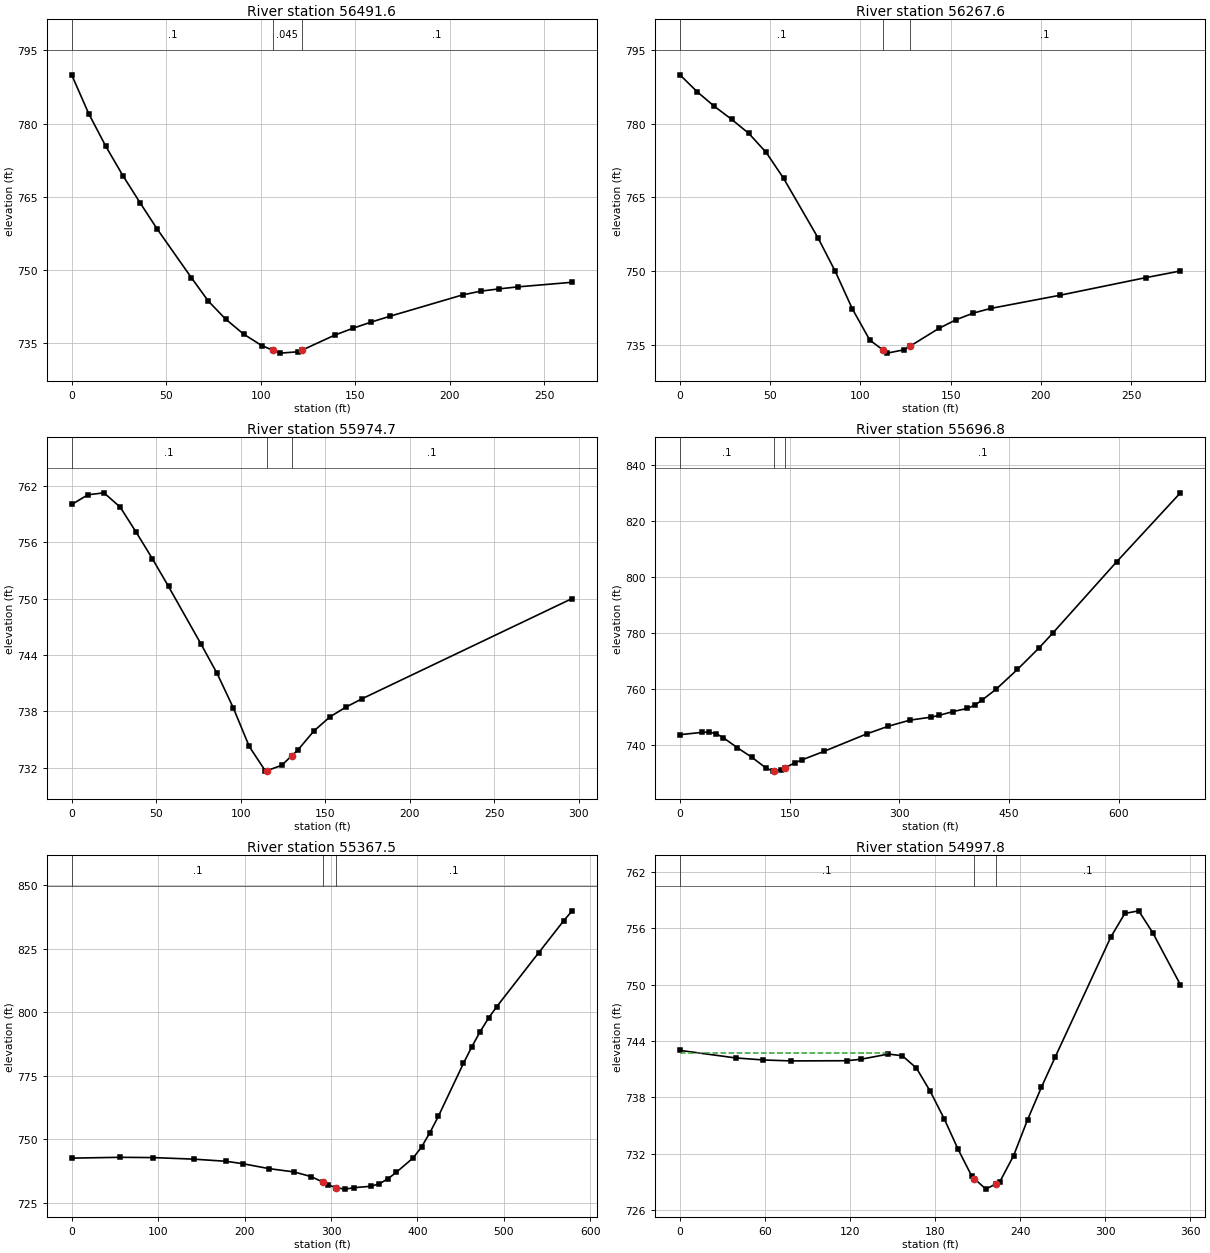
Type RM Length L Ch R = 1 ,56491.6 ,247.7,224,200.4
XS GIS Cut Line= 3
     1533250.916      315114.499     1533313.174      315166.912
     1533395.743      315330.727
#Sta/Elev= 24
       0  789.98       9  782.03    18.1   775.3    27.1  769.32    36.2  763.75
    45.2   758.4    63.3  748.42    72.3  743.61    81.4  739.94      91  736.84
   100.7  734.46   106.6  733.54   110.4  732.95     120  733.23   121.6  733.51
   139.3  736.66     149  738.07   158.6  739.33   168.3   740.5   206.9  744.89
   216.6  745.66   226.2  746.12   235.9  746.52   264.8  747.47
#Mann= 3 , 0 , 0
       0      .1       0   106.6    .045       0   121.6      .1       0
Bank Sta=106.6,121.6
XS Rating Curve= 0 ,0
Exp/Cntr=0.3,0.1

Type RM Length L Ch R = 1 ,56267.6 ,293.6,292.9,292.2
XS GIS Cut Line= 2
     1533128.911      315376.782     1533404.934      315403.522
#Sta/Elev= 22
       0     790     9.6  786.53    19.1  783.57    28.7  780.91    38.2  778.04
    47.8  774.17    57.4  768.92    76.5  756.76    86.1   749.9    95.6  742.23
   105.2  735.91   112.5  733.89   114.8  733.25   124.3  733.94   127.5  734.66
   143.4  738.28     153  740.06   162.6  741.42   172.1  742.36   210.4  745.04
   258.2  748.65   277.3     750
#Mann= 3 , 0 , 0
       0      .1       0   112.5    .045       0   127.5      .1       0
Bank Sta=112.5,127.5
XS Rating Curve= 0 ,0
Exp/Cntr=0.3,0.1

Type RM Length L Ch R = 1 ,55974.7 ,278.5,277.8,277.2
XS GIS Cut Line= 2
     1533103.245      315672.057     1533398.828      315691.742
#Sta/Elev= 21
       0     760     9.6  761.03    19.1  761.24    28.7  759.72    38.2  757.04
    47.8  754.22    57.3  751.28    76.4   745.2      86  742.05    95.6  738.39
   105.1  734.26   114.7  731.64   115.4  731.68   124.2  732.25   130.4   733.3
   133.8  733.87   143.3   735.9   152.9  737.42   162.4  738.46     172  739.35
   296.2     750
#Mann= 3 , 0 , 0
       0      .1       0   115.4    .045       0   130.4      .1       0
Bank Sta=115.4,130.4
XS Rating Curve= 0 ,0
Exp/Cntr=0.3,0.1

Type RM Length L Ch R = 1 ,55696.8 ,305.4,329.3,352
XS GIS Cut Line= 3
     1533072.827      315952.255     1533504.762      315968.737
     1533734.941      316070.961
#Sta/Elev= 30
       0  743.79    29.5  744.61    39.3  744.73    49.1  744.19    58.9  742.79
    78.6  739.14    98.2  735.77   117.9  731.87   127.7  730.81   128.2  730.83
   137.5  731.23   143.2  731.96   157.2  733.77     167  734.84   196.5  737.81
   255.4  744.09   284.9  746.82   314.4  748.98   343.8  750.07   353.7  750.66
   373.3  752.03     393  753.18   402.8  754.26   412.6  756.06   432.2     760
   461.3  767.04   490.4  774.59   509.7  780.02   596.9   805.4   684.1     830
#Mann= 3 , 0 , 0
       0      .1       0   128.2    .045       0   143.2      .1       0
Bank Sta=128.2,143.2
XS Rating Curve= 0 ,0
Exp/Cntr=0.3,0.1

Type RM Length L Ch R = 1 ,55367.5 ,330.7,369.7,408.2
XS GIS Cut Line= 4
     1533091.893      315997.636     1533086.101      316176.258
     1533196.177       316351.19     1533191.791      316544.647
#Sta/Elev= 30
       0  742.62    56.4  742.94    94.1  742.83   141.1  742.22   178.7  741.37
   198.4   740.4   227.9   738.5   257.4  737.17   277.1  735.33   290.8  733.13
   296.8   732.1   305.8  730.95   316.5  730.41   326.4  730.98     346  731.53
   355.9  732.52   365.7  734.46   375.6  737.06   395.1  742.74   404.8  747.05
   414.4  752.68   424.1  759.06   453.1  779.91   462.8  786.45   472.5  792.46
   482.2  797.75   491.8  802.32   540.2  823.51   569.2  836.13   578.9     840
#Mann= 3 , 0 , 0
       0      .1       0   290.8    .045       0   305.8      .1       0
Bank Sta=290.8,305.8
XS Rating Curve= 0 ,0
Exp/Cntr=0.3,0.1

Type RM Length L Ch R = 1 ,54997.8 ,260.7,272.1,283.4
XS GIS Cut Line= 2
     1533105.414      315986.737     1532798.289      316160.592
#Sta/Elev= 26
       0     743    39.2   742.2    58.8  741.98    78.4  741.88   117.6   741.9
   127.4  742.05     147  742.61   156.8  742.43   166.7  741.13   176.5  738.64
   186.3  735.73   196.1  732.48   205.9  729.57   207.6  729.34   215.7  728.22
   222.6  728.76   225.5  728.98   235.3  731.79   245.1   735.6   254.9  739.07
   264.7  742.32   303.9  755.09   313.7  757.59   323.5  757.87   333.3  755.56
   352.9     750
#Mann= 3 , 0 , 0
       0      .1       0   207.6    .045       0   222.6      .1       0
#XS Ineff= 2 , 0
          147.04  742.74
Permanent Ineff=
       F       F
Bank Sta=207.6,222.6
XS Rating Curve= 0 ,0
Exp/Cntr=0.3,0.1

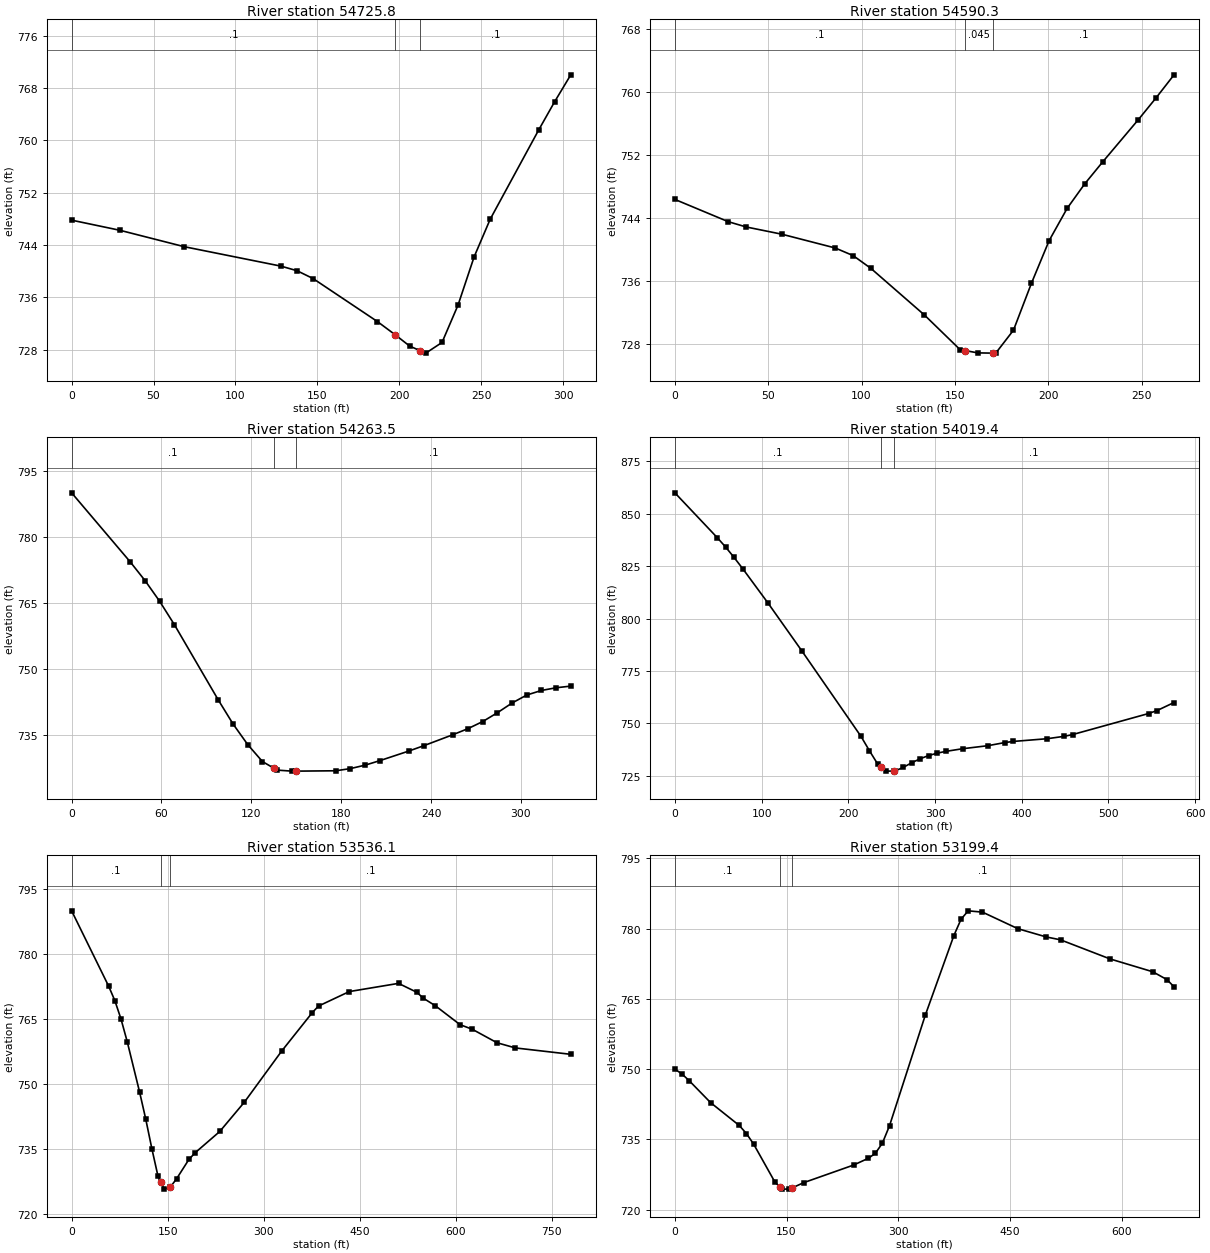
Type RM Length L Ch R = 1 ,54725.8 ,135.2,135.5,135.8
XS GIS Cut Line= 2
     1533027.688      315837.672     1532723.038      315842.143
#Sta/Elev= 18
       0  747.79    29.5  746.24    68.8  743.73   127.8  740.76   137.6  740.06
   147.4  738.86   186.7  732.28   197.6  730.25   206.4  728.53   212.6  727.85
   216.2  727.46   226.1  729.09   235.9  734.82   245.7  742.18   255.5  747.93
     285  761.53   294.8  765.88   304.7  770.01
#Mann= 3 , 0 , 0
       0      .1       0   197.6    .045       0   212.6      .1       0
Bank Sta=197.6,212.6
XS Rating Curve= 0 ,0
Exp/Cntr=0.3,0.1

Type RM Length L Ch R = 1 ,54590.3 ,346.8,326.8,306.8
XS GIS Cut Line= 2
     1532977.773      315705.599     1532710.412      315705.599
#Sta/Elev= 22
       0  746.33    28.6   743.5    38.2  742.83    57.3  741.91    85.9  740.16
    95.5  739.19     105  737.57   133.7  731.64   152.8  727.24   155.4  727.13
   162.3  726.83   170.4   726.8   171.9   726.8   181.4  729.72     191  735.67
   200.5   741.1   210.1  745.18   219.6  748.32   229.2   751.1   248.3  756.47
   257.8  759.24   267.4  762.16
#Mann= 3 , 0 , 0
       0      .1       0   155.4    .045       0   170.4      .1       0
Bank Sta=155.4,170.4
XS Rating Curve= 0 ,0
Exp/Cntr=0.3,0.1

Type RM Length L Ch R = 1 ,54263.5 ,265.6,244.2,222.7
XS GIS Cut Line= 2
      1532915.12      315278.357      1532687.41      315521.699
#Sta/Elev= 28
       0     790    39.2  774.29      49  770.08    58.8  765.36    68.6  760.07
      98  742.92   107.8   737.5   117.6  732.82   127.4  728.98   134.9  727.49
   137.2  727.03     147   726.8   149.9   726.8   176.4  726.88   186.2  727.38
     196  728.16   205.8  729.18   225.4  731.39   235.2  732.58   254.8   735.1
   264.6  736.44   274.5  738.06   284.3  740.06   294.1  742.27   303.9  744.08
   313.7  745.12   323.5  745.73   333.3  746.11
#Mann= 3 , 0 , 0
       0      .1       0   134.9    .045       0   149.9      .1       0
Bank Sta=134.9,149.9
XS Rating Curve= 0 ,0
Exp/Cntr=0.3,0.1

Type RM Length L Ch R = 1 ,54019.4 ,512.4,483.3,454.1
XS GIS Cut Line= 2
     1532558.479      315076.976     1532676.589      315640.447
#Sta/Elev= 30
       0     860    48.8  838.66    58.6  834.11    68.3  829.17    78.1  823.91
   107.3   807.5   146.4  784.64   214.7  743.83   224.4     737   234.2  730.46
   237.4  729.42     244  727.28   252.4  727.32   253.7  727.33   263.5  729.08
   273.2  731.29     283  733.19   292.7  734.72   302.5  735.84   312.2  736.68
   331.8  737.96     361  739.41   380.6  740.91   390.3  741.44   429.4  742.74
   448.9  743.87   458.6   744.7   546.4  754.76   556.2  756.18   575.7     760
#Mann= 3 , 0 , 0
       0      .1       0   237.4    .045       0   252.4      .1       0
Bank Sta=237.4,252.4
XS Rating Curve= 0 ,0
Exp/Cntr=0.3,0.1

Type RM Length L Ch R = 1 ,53536.1 ,332.3,336.7,340.9
XS GIS Cut Line= 3
      1532279.52      315708.058     1532664.032      315738.466
     1532797.255       316109.35
#Sta/Elev= 30
       0  789.98    57.9  772.59    67.5  769.28    77.1  765.05    86.8  759.84
   106.1  748.24   115.7  742.01   125.4  735.09     135  728.74   139.4  727.39
   144.6   725.8   154.4  726.32   163.9  728.17   183.2  732.64   192.9  734.18
   231.4  739.09     270  745.88   327.9  757.59   376.1  766.53   385.7  768.02
   433.8  771.36   510.7  773.25   539.5  771.18   549.1  769.86   568.3  768.08
   606.8  763.73     626  762.66   664.5  759.56   693.3  758.36   779.8  756.89
#Mann= 3 , 0 , 0
       0      .1       0   139.4    .045       0   154.4      .1       0
Bank Sta=139.4,154.4
XS Rating Curve= 0 ,0
Exp/Cntr=0.3,0.1

Type RM Length L Ch R = 1 ,53199.4 ,188.8,192.6,196.6
XS GIS Cut Line= 3
     1532196.495      316004.514     1532585.442      316112.329
     1532750.597      316322.024
#Sta/Elev= 30
       0     750     9.6  748.95    19.2  747.53      48  742.84    86.5  737.96
    96.1  736.24   105.7  734.01   134.5  725.84   141.8  724.75   144.2  724.39
   153.8  724.37   156.8  724.58     173  725.75   240.2  729.52   259.5  730.93
   269.1  731.98   278.7  734.17   288.3   737.9   336.3  761.48   374.8  778.53
   384.4     782     394   783.8   413.2  783.52   460.8  779.98   498.9  778.22
     518  777.61   584.7  773.52   641.9  770.79     661  769.11   670.5  767.57
#Mann= 3 , 0 , 0
       0      .1       0   141.8    .045       0   156.8      .1       0
Bank Sta=141.8,156.8
XS Rating Curve= 0 ,0
Exp/Cntr=0.3,0.1