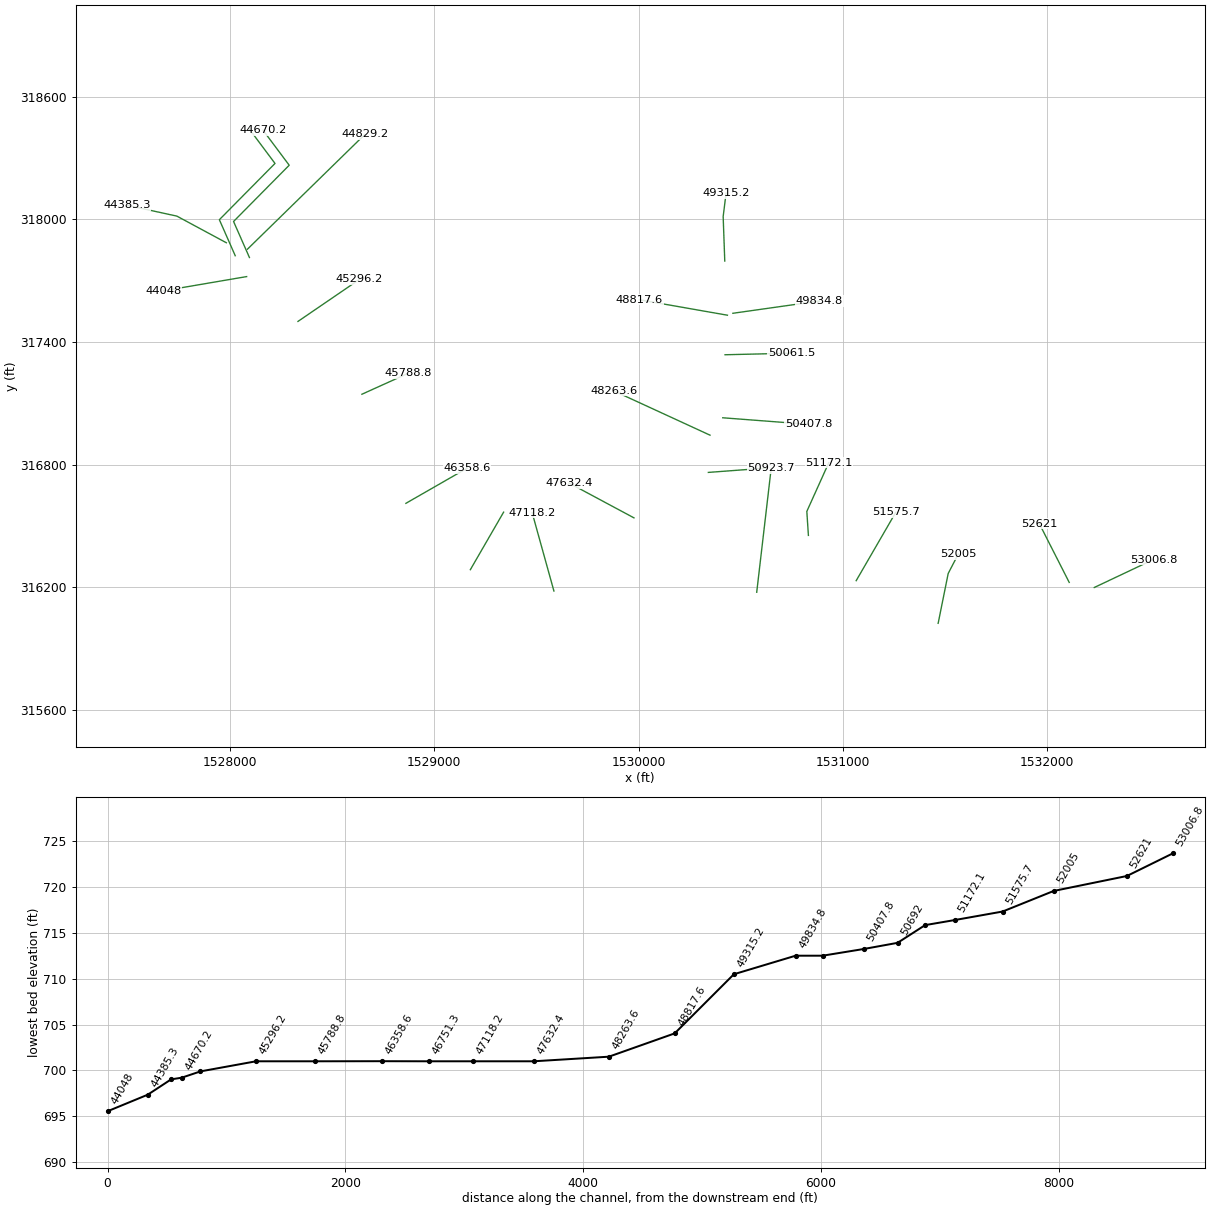
HEC-RAS study McKimCr.prj: McKimCr

--- McKimCr.g01 (geometry) --- (continued)

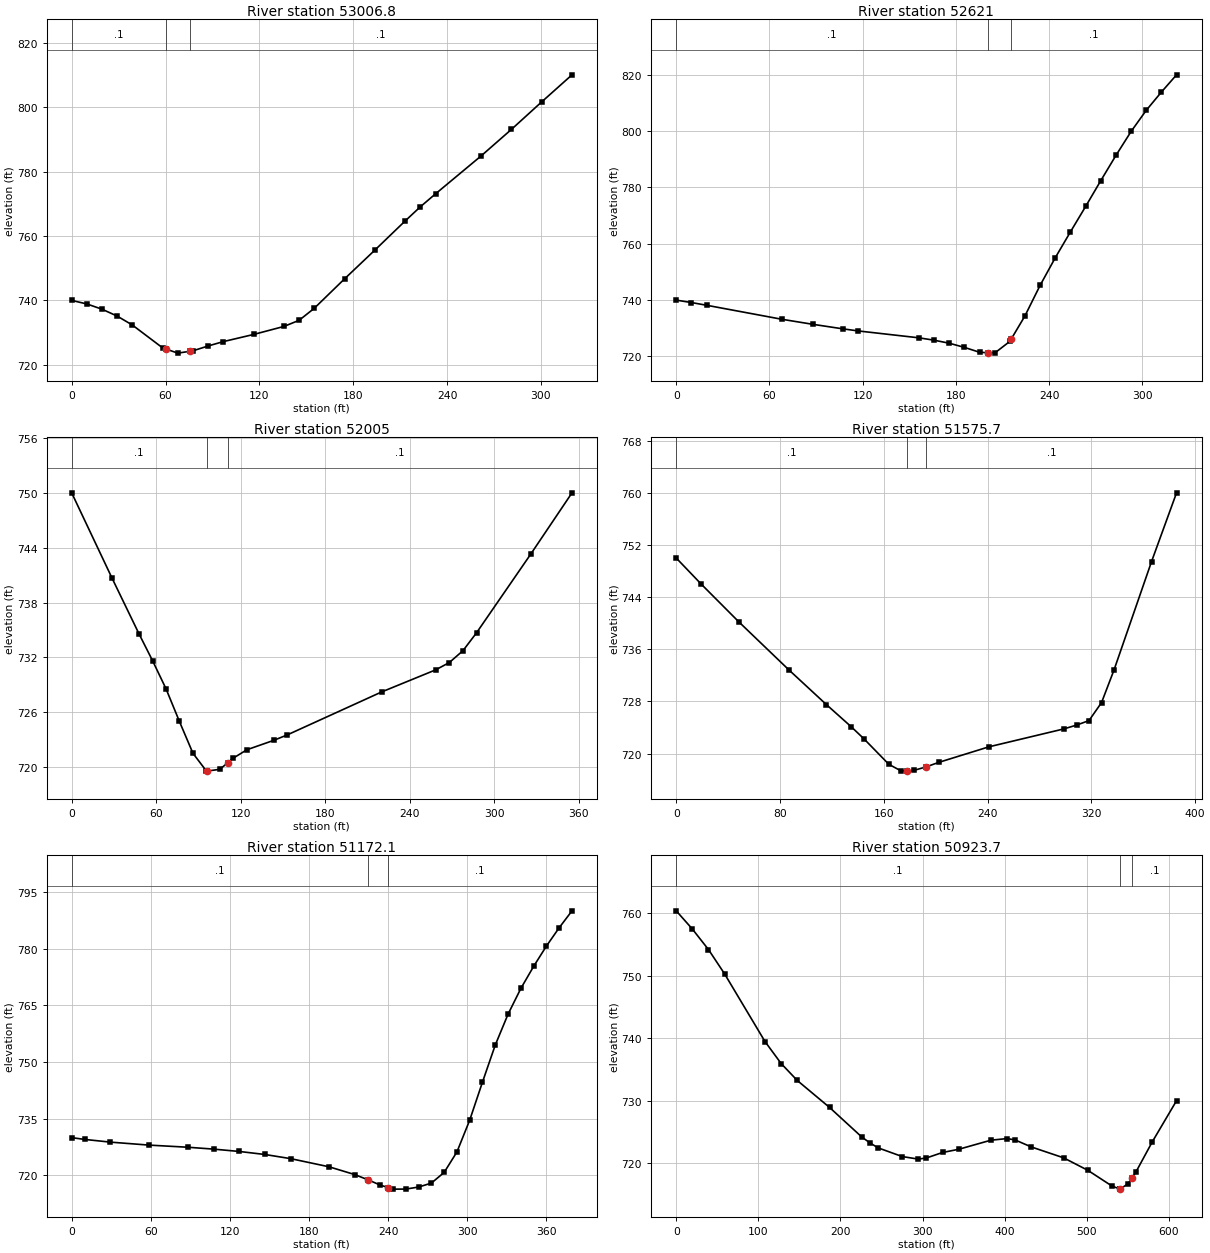
Type RM Length L Ch R = 1 ,53006.8 ,348.3,385.7,422.4
XS GIS Cut Line= 2
     1532229.863      316199.737     1532519.109      316336.469
#Sta/Elev= 25
       0     740     9.7   738.9    19.4  737.27    29.1  735.13    38.8  732.36
    58.2  725.25    60.4  724.88    67.9  723.64    75.4   724.2    77.6  724.37
    87.3  725.87      97  727.22   116.3  729.43   135.7  731.92   145.4  733.82
   155.1  737.55   174.5   746.7   193.9  755.63   213.3  764.69     223  769.08
   232.7  773.09   261.8  784.84   281.2  793.08   300.6  801.64   319.9     810
#Mann= 3 , 0 , 0
       0      .1       0    60.4    .045       0    75.4      .1       0
Bank Sta=60.4,75.4
XS Rating Curve= 0 ,0
Exp/Cntr=0.3,0.1

Type RM Length L Ch R = 1 ,52621   ,631.6,616,601
XS GIS Cut Line= 2
     1532107.187      316224.701     1531961.121      316511.705
#Sta/Elev= 27
       0     740     9.8  739.14    19.5  738.18    68.3  733.17    87.8  731.42
   107.4  729.79   117.1  729.06   156.1  726.62   165.9  725.78   175.7   724.7
   185.4  723.23   195.2  721.49   200.6  721.32   204.9  721.18   214.7  725.34
   215.6  726.18   224.4  734.36   234.2  745.25     244   755.1   253.7  764.22
   263.5  773.26   273.2  782.38     283  791.38   292.8  799.92   302.5  807.39
   312.3   813.9     322  819.99
#Mann= 3 , 0 , 0
       0      .1       0   200.6    .045       0   215.6      .1       0
Bank Sta=200.6,215.6
XS Rating Curve= 0 ,0
Exp/Cntr=0.3,0.1

Type RM Length L Ch R = 1 ,52005   ,436.7,429.3,422.3
XS GIS Cut Line= 3
     1531465.961      316024.578     1531515.174      316268.371
     1531564.386      316362.866
#Sta/Elev= 22
       0     750    28.7  740.65    47.8  734.57    57.4  731.64      67  728.55
    76.5  724.98    86.1   721.5    95.7  719.55    95.9  719.55   105.2  719.75
   110.9  720.48   114.8  720.98   124.4  721.89   143.5  722.92     153  723.51
     220  728.21   258.4  730.63   268.1  731.43   277.8  732.73   287.4  734.68
   326.2  743.36   355.2     750
#Mann= 3 , 0 , 0
       0      .1       0    95.9    .045       0   110.9      .1       0
Bank Sta=95.9,110.9
XS Rating Curve= 0 ,0
Exp/Cntr=0.3,0.1

Type RM Length L Ch R = 1 ,51575.7 ,400.7,403.5,406.1
XS GIS Cut Line= 2
     1531064.946       316233.08     1531258.358      316566.815
#Sta/Elev= 21
       0     750    19.3  745.99    48.2  740.22    86.8  732.85   115.7  727.53
     135   724.1   144.6  722.29   163.9  718.36   173.6  717.31   177.6  717.36
   183.2  717.42   192.6  717.96   202.5  718.66   241.1  721.04   298.9  723.79
   308.6  724.37   318.2  725.06   327.9  727.83   337.5  732.83   366.4  749.44
   385.7     760
#Mann= 3 , 0 , 0
       0      .1       0   177.6    .045       0   192.6      .1       0
Bank Sta=177.6,192.6
XS Rating Curve= 0 ,0
Exp/Cntr=0.3,0.1

Type RM Length L Ch R = 1 ,51172.1 ,241.3,248.4,255.2
XS GIS Cut Line= 3
     1530831.168      316454.489     1530823.453      316571.756
     1530931.241      316810.564
#Sta/Elev= 29
       0     730     9.8  729.53    29.4  728.81    58.8  728.02    88.1  727.46
   107.7  726.96   127.2  726.34   146.6  725.54     166  724.45   195.2  722.29
   214.6  720.24   224.8  718.84     234  717.46   239.8  716.81   243.7  716.38
   253.4  716.39   263.1  716.93   272.8  717.97   282.5  720.79   292.2  726.21
   301.9  734.62   311.6   744.7   321.3   754.5     331  762.66   340.7  769.46
   350.4   775.3   360.1  780.67   369.8  785.53   379.5  789.99
#Mann= 3 , 0 , 0
       0      .1       0   224.8    .045       0   239.8      .1       0
Bank Sta=224.8,239.8
XS Rating Curve= 0 ,0
Exp/Cntr=0.3,0.1

Type RM Length L Ch R = 1 ,50923.7 ,264.2,231.7,199.4
XS GIS Cut Line= 2
     1530578.288      316176.624     1530649.034       316781.77
#Sta/Elev= 30
       0  760.42    19.6  757.51    39.3  754.21      59   750.3   108.1  739.48
   127.8  735.95   147.4  733.24   186.7  728.92     226  724.18   235.8  723.25
   245.7  722.45   275.2  721.05   294.8  720.64   304.6  720.82   324.3   721.7
   343.9  722.21   383.2  723.67   402.9  723.93   412.7  723.71   432.4  722.59
   471.7  720.85   501.2  718.85   530.6  716.33   540.1  715.85   540.5  715.83
   550.3   716.7   555.1  717.65   560.1  718.64   579.8  723.42   609.3     730
#Mann= 3 , 0 , 0
       0      .1       0   540.1    .045       0   555.1      .1       0
Bank Sta=540.1,555.1
XS Rating Curve= 0 ,0
Exp/Cntr=0.3,0.1

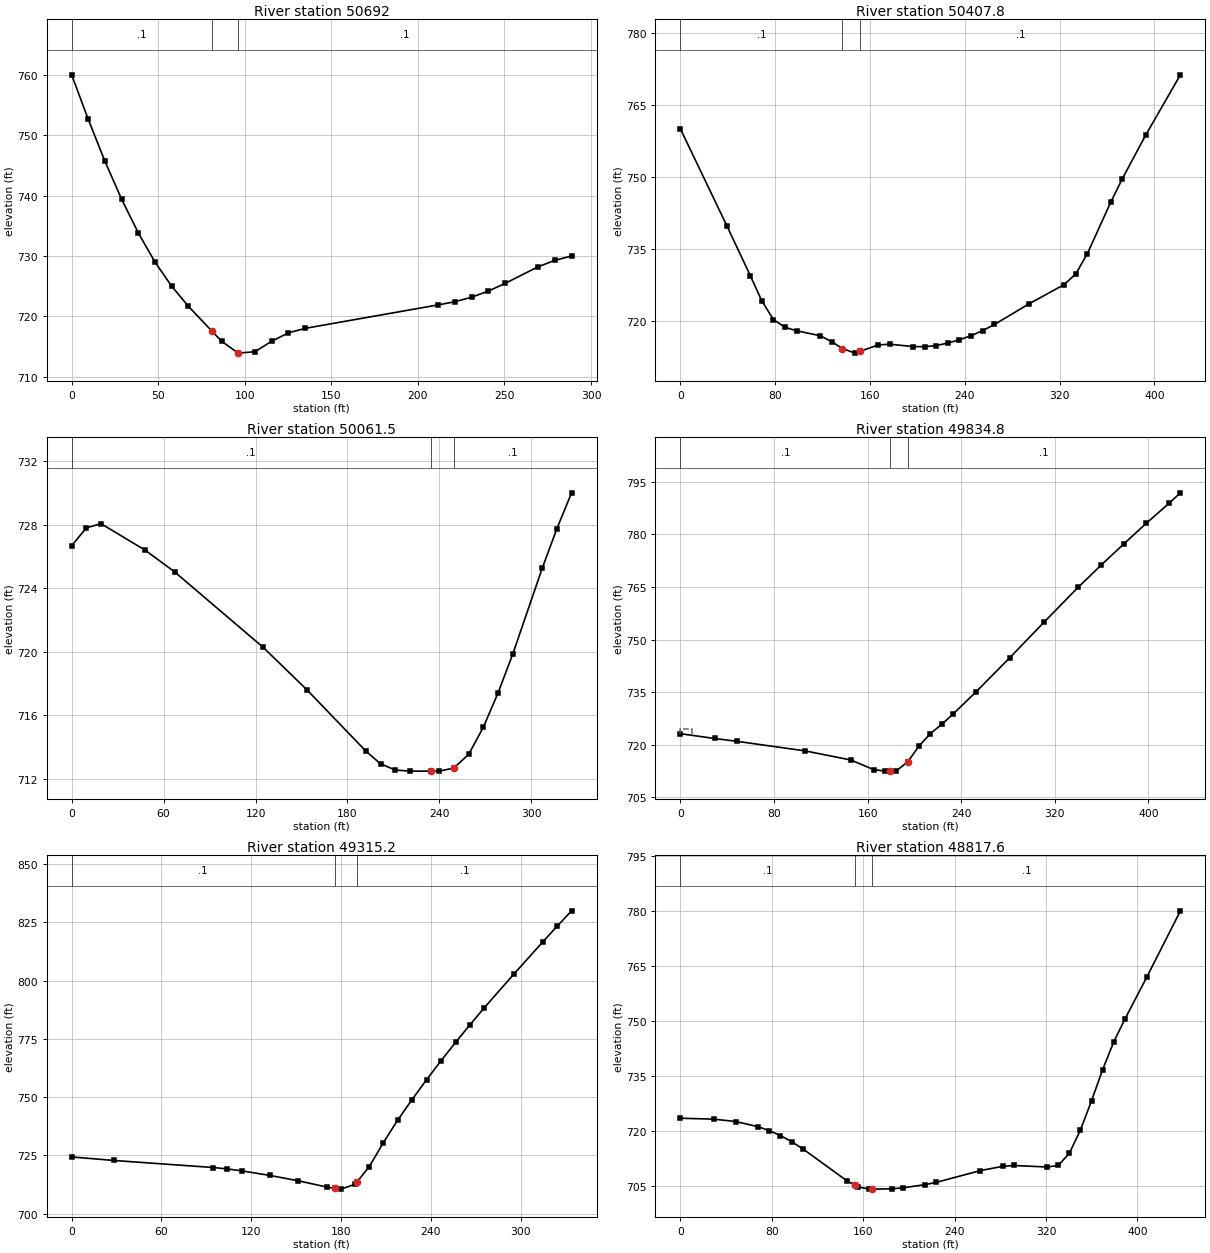
Type RM Length L Ch R = 1 ,50692   ,287.4,284.2,280.9
XS GIS Cut Line= 2
     1530341.765      316762.425     1530629.733      316783.875
#Sta/Elev= 23
       0  760.02     9.6  752.63    19.2  745.71    28.9  739.38    38.5  733.83
    48.1  729.01    57.8  724.98    67.4  721.67    81.2  717.49    86.6  715.88
    96.2   713.9   105.9  714.14   115.5  715.86   125.1  717.25   134.8     718
   211.8   721.9   221.4  722.42     231  723.16   240.6  724.17   250.3  725.44
   269.5  728.22   279.1  729.27   288.8     730
#Mann= 3 , 0 , 0
       0      .1       0    81.2    .045       0    96.2      .1       0
Bank Sta=81.2,96.2
XS Rating Curve= 0 ,0
Exp/Cntr=0.3,0.1

Type RM Length L Ch R = 1 ,50407.8 ,345.1,346.4,347.6
XS GIS Cut Line= 2
     1530412.021      317029.529     1530832.807      316997.439
#Sta/Elev= 30
       0     760    39.3  739.72    58.9  729.42    68.7  724.12    78.5  720.22
    88.3  718.61    98.1  717.89   117.8  716.87   127.6  715.63   136.7  714.19
   147.2  713.23   151.7  713.62   166.8  714.93   176.6  715.09   196.3   714.6
   206.1  714.57   215.9  714.81   225.7  715.33   235.5  716.02   245.4  716.88
   255.2  717.94     265  719.21   294.4  723.54   323.9  727.54   333.7  729.77
   343.5  734.02   363.1  744.69   372.9   749.6   392.6  758.69     422  771.31
#Mann= 3 , 0 , 0
       0      .1       0   136.7    .045       0   151.7      .1       0
Bank Sta=136.7,151.7
XS Rating Curve= 0 ,0
Exp/Cntr=0.3,0.1

Type RM Length L Ch R = 1 ,50061.5 ,224.1,226.7,229.2
XS GIS Cut Line= 2
     1530423.123      317337.649     1530749.354      317345.282
#Sta/Elev= 21
       0  726.67     9.6   727.8    19.2  728.06      48  726.39    67.2  725.03
   124.8   720.3   153.6  717.61     192  713.76   201.6  712.96   211.2  712.57
   220.8   712.5   234.3   712.5   239.9   712.5   249.3  712.69   259.1  713.55
   268.7  715.26   278.3  717.42   287.9  719.86   307.1  725.25   316.7  727.75
   326.3     730
#Mann= 3 , 0 , 0
       0      .1       0   234.3    .045       0   249.3      .1       0
Bank Sta=234.3,249.3
XS Rating Curve= 0 ,0
Exp/Cntr=0.3,0.1

Type RM Length L Ch R = 1 ,49834.8 ,486.4,519.5,552.6
XS GIS Cut Line= 2
     1530461.714      317540.408     1530884.891      317600.303
#Sta/Elev= 23
       0  723.16    29.1   721.8    48.6  720.98   106.8  718.25   145.7  715.67
   165.1  712.94   174.8   712.5   179.4  712.56   184.6  712.62   194.4  715.17
     204   719.7   213.7   723.2   223.4  725.85   233.1  728.78   252.6  735.06
   281.7  744.87   310.8  754.94     340  764.88   359.4  771.13   378.8  777.17
   398.2  783.11   417.7  788.81   427.4  791.79
#Mann= 3 , 0 , 0
       0      .1       0   179.4    .045       0   194.4      .1       0
#XS Ineff= 2 , 0
            9.68  724.64
Permanent Ineff=
       F       F
Bank Sta=179.4,194.4
XS Rating Curve= 0 ,0
Exp/Cntr=0.3,0.1

Type RM Length L Ch R = 1 ,49315.2 ,466.9,497.6,528.1
XS GIS Cut Line= 3
     1530421.977      317795.714     1530414.138      318013.248
     1530428.522      318128.706
#Sta/Elev= 25
       0   724.3    28.4  722.78    94.6  719.76   104.1  719.14   113.6  718.34
   132.5  716.35   151.4  714.06   170.4  711.38   175.8  710.86   179.8  710.48
   189.3  712.54   190.8  713.73   198.8   720.1   208.2   730.4   217.7  740.02
   227.4  748.93   237.1  757.46   246.8  765.64   256.5  773.52   266.2  781.14
   275.8  788.48   295.2  802.66   314.6  816.55   324.3  823.37     334     830
#Mann= 3 , 0 , 0
       0      .1       0   175.8    .045       0   190.8      .1       0
Bank Sta=175.8,190.8
XS Rating Curve= 0 ,0
Exp/Cntr=0.3,0.1

Type RM Length L Ch R = 1 ,48817.6 ,559.8,554,548.2
XS GIS Cut Line= 2
     1530434.998      317530.957     1530003.876      317606.583
#Sta/Elev= 30
       0  723.39    29.2  723.14    48.6  722.48    68.1  721.06    77.8  720.01
    87.5  718.66    97.3     717     107  715.06   145.9  706.27   152.8  705.11
   155.6  704.64   165.4  704.04   167.8  704.04   184.8  704.12   194.5  704.38
     214  705.26   223.7  705.87   262.6   709.1   282.1  710.26   291.8  710.49
     321  710.08   330.7  710.49   340.4  713.79   350.2   720.2   359.9  728.18
   369.6  736.65   379.3  744.22   389.1  750.44   408.5  762.06   437.7     780
#Mann= 3 , 0 , 0
       0      .1       0   152.8    .045       0   167.8      .1       0
Bank Sta=152.8,167.8
XS Rating Curve= 0 ,0
Exp/Cntr=0.3,0.1

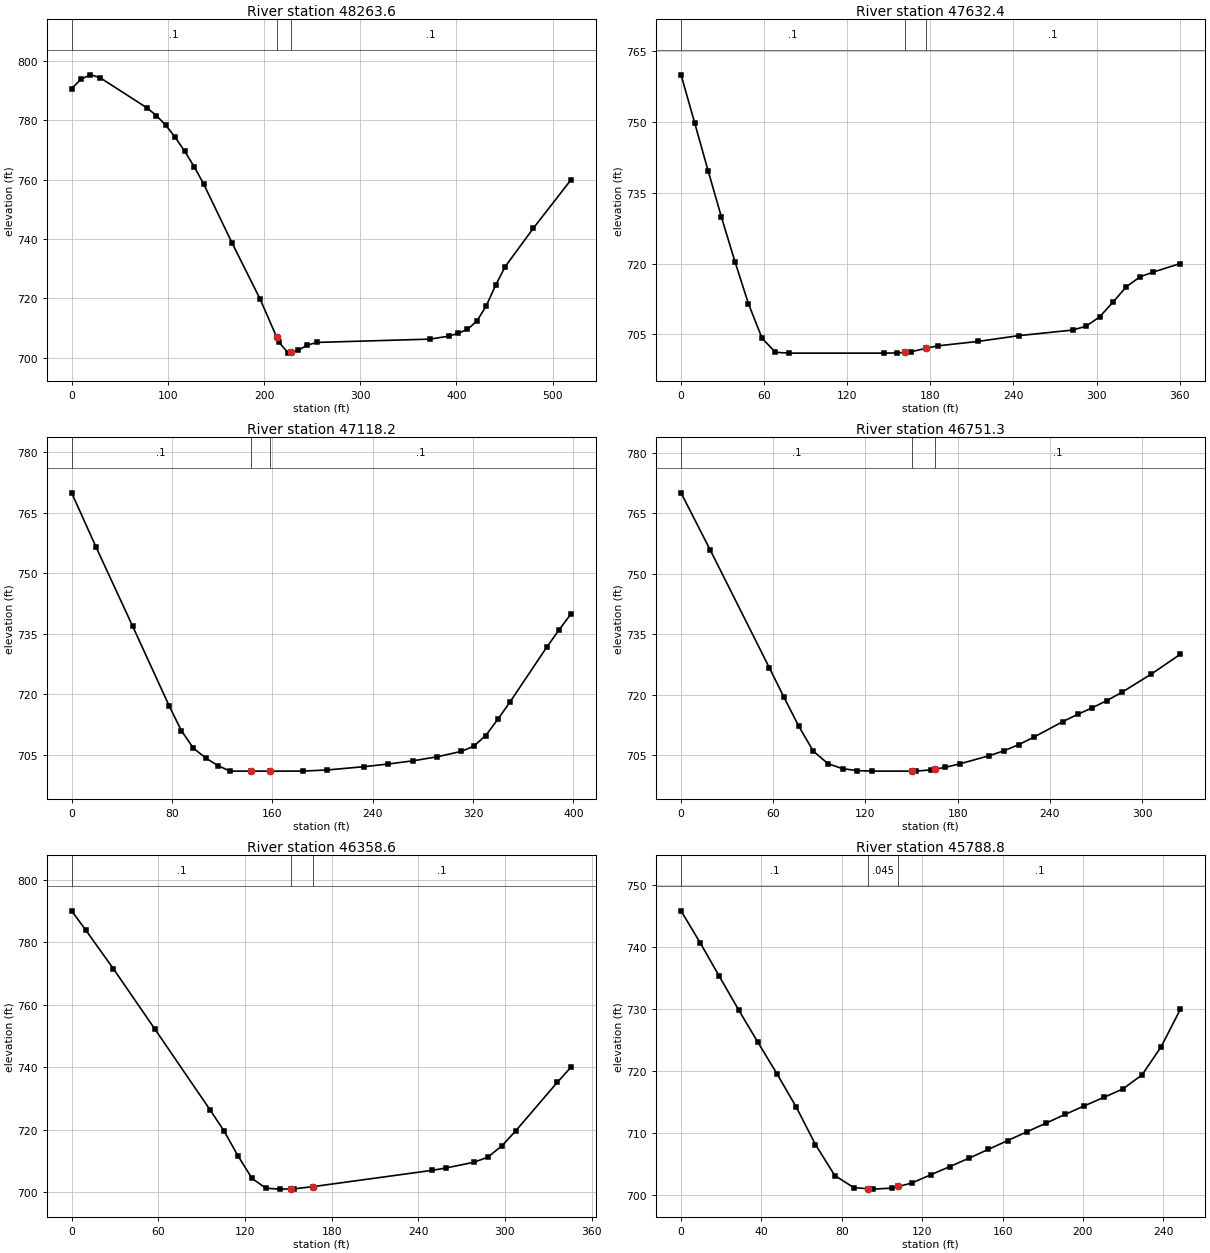
Type RM Length L Ch R = 1 ,48263.6 ,619.5,631.3,649.2
XS GIS Cut Line= 2
     1530349.881      316944.456     1529878.149      317161.445
#Sta/Elev= 30
       0  790.75     9.8  793.94    19.6  795.39    29.4  794.46    78.4  784.22
    88.2  781.62      98  778.33   107.8  774.28   117.6  769.56   127.4   764.4
   137.2  758.59   166.6  738.78   195.9  719.76     213     707   215.5  705.19
   225.3   701.5     228  701.75   235.1  702.41   244.9  704.16   254.7  705.11
   372.3  706.22   391.9  707.22   401.7  708.15   411.5  709.53   421.3  712.31
   431.1   717.5   440.9  724.49   450.7  730.67   480.1  743.68   519.2     760
#Mann= 3 , 0 , 0
       0      .1       0     213    .045       0     228      .1       0
Bank Sta=213,228
XS Rating Curve= 0 ,0
Exp/Cntr=0.3,0.1

Type RM Length L Ch R = 1 ,47632.4 ,545.8,514.2,475.6
XS GIS Cut Line= 2
     1529977.775      316540.164     1529659.884      316710.464
#Sta/Elev= 25
       0  760.01     9.8  749.88    19.5  739.72    29.2  729.82      39  720.34
    48.7  711.46    58.5  704.15    68.2  701.18      78     701   146.2     701
     156  701.03   161.7  701.17   165.7  701.27   176.7     702   185.2  702.54
   214.4  703.48   243.7   704.7   282.7  705.89   292.4   706.7   302.2  708.68
   311.9  711.81   321.6  715.09   331.4  717.17   341.1   718.2   360.6     720
#Mann= 3 , 0 , 0
       0      .1       0   161.7    .045       0   176.7      .1       0
Bank Sta=161.7,176.7
XS Rating Curve= 0 ,0
Exp/Cntr=0.3,0.1

Type RM Length L Ch R = 1 ,47118.2 ,390.2,366.8,341.9
XS GIS Cut Line= 2
     1529586.044      316182.544     1529479.396      316566.105
#Sta/Elev= 25
       0     770    19.4  756.59    48.6  736.95    77.7  717.21    87.4  711.06
    97.1  706.68   106.8  704.28   116.5  702.39   126.2     701   142.8     701
   157.8     701   184.5  701.01   203.9  701.29     233   702.1   252.5  702.77
   271.9  703.55   291.3  704.55   310.7   705.9   320.4  707.16   330.1  709.83
   339.8  713.87   349.6  718.22   378.7  731.72   388.4  735.96   398.1     740
#Mann= 3 , 0 , 0
       0      .1       0   142.8    .045       0   157.8      .1       0
Bank Sta=142.8,157.8
XS Rating Curve= 0 ,0
Exp/Cntr=0.3,0.1

Type RM Length L Ch R = 1 ,46751.3 ,400.1,392.7,386.8
XS GIS Cut Line= 2
     1529177.207      316286.841     1529339.981      316568.151
#Sta/Elev= 27
       0  770.01    19.1  755.75    57.4  726.69    66.9  719.38    76.5  712.23
      86  705.99    95.6  702.85   105.2   701.6   114.7  701.13   124.3     701
   150.1     701     153     701   162.5  701.31   165.1  701.48   172.1  701.95
   181.6  702.82   200.7  704.84   210.3  706.06   219.9  707.59   229.4  709.38
   248.5  713.29   258.1  715.07   267.6  716.71   277.2  718.51   286.8  720.52
   305.9  725.03     325     730
#Mann= 3 , 0 , 0
       0      .1       0   150.1    .045       0   165.1      .1       0
Bank Sta=150.1,165.1
XS Rating Curve= 0 ,0
Exp/Cntr=0.3,0.1

Type RM Length L Ch R = 1 ,46358.6 ,572.4,569.9,567.4
XS GIS Cut Line= 2
     1528861.896      316611.291     1529161.852      316783.295
#Sta/Elev= 21
       0  789.99     9.6  783.94    28.8  771.54    57.6   752.2      96  726.26
   105.6  719.54   115.3  711.55   124.9  704.44   134.5  701.31   144.1  701.01
     152  701.07   153.7  701.08     167   701.8   249.7  707.02   259.3  707.78
   278.5   709.6   288.1  711.21   297.8   714.8   307.4  719.59   336.2  735.11
   345.8  740.01
#Mann= 3 , 0 , 0
       0      .1       0     152    .045       0     167      .1       0
Bank Sta=152,167
XS Rating Curve= 0 ,0
Exp/Cntr=0.3,0.1

Type RM Length L Ch R = 1 ,45788.8 ,488.6,492.6,496.5
XS GIS Cut Line= 2
     1528646.609      317144.574     1528873.073      317246.857
#Sta/Elev= 29
       0  745.84     9.6  740.65    19.1  735.26    28.7  729.86    38.2  724.68
    47.8  719.55    57.3  714.24    66.9  708.18    76.5  703.19      86  701.24
    93.2  701.06    95.6     701   105.1  701.17   108.2  701.43   114.7  701.97
   124.2   703.3   133.8  704.64   143.4     706   152.9   707.4   162.5  708.82
     172  710.22   181.6  711.63   191.2  713.05   200.7  714.42   210.3  715.77
   219.8  717.13   229.4  719.41   238.9  723.93   248.5     730
#Mann= 3 , 0 , 0
       0      .1       0    93.2    .045       0   108.2      .1       0
Bank Sta=93.2,108.2
XS Rating Curve= 0 ,0
Exp/Cntr=0.3,0.1

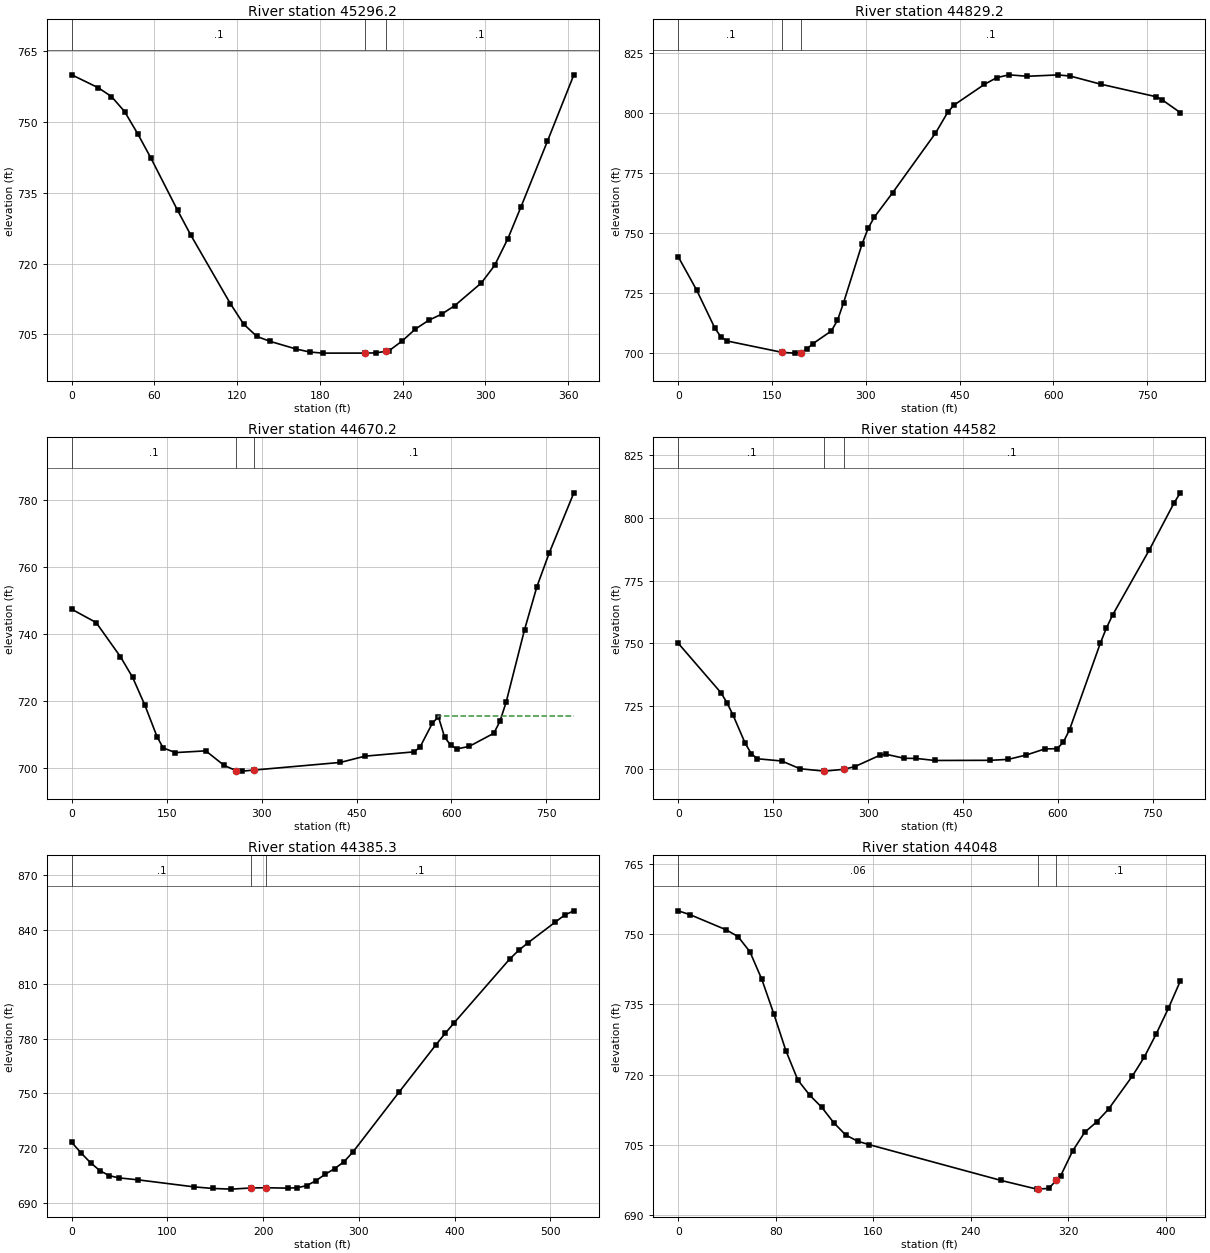
Type RM Length L Ch R = 1 ,45296.2 ,463,467,470.8
XS GIS Cut Line= 2
      1528333.96      317500.676     1528634.721      317706.054
#Sta/Elev= 30
       0     760    19.2  757.26    28.8   755.4    38.3  752.22    47.9  747.47
    57.5   742.3    76.7   731.3    86.3  726.04     115  711.51   124.6  707.18
   134.2  704.55   143.8   703.5   162.9  701.86   172.5  701.24   182.1     701
     213  701.01   220.4  701.05     228  701.39     230  701.48   239.6  703.56
   249.2  706.09   258.8  707.94   268.4  709.28   277.9  711.09   297.1  715.88
   306.7  719.58   316.3  725.24   325.9  732.04     345   745.9   364.2     760
#Mann= 3 , 0 , 0
       0      .1       0     213    .045       0     228      .1       0
Bank Sta=213,228
XS Rating Curve= 0 ,0
Exp/Cntr=0.3,0.1

Type RM Length L Ch R = 1 ,44829.2 ,166.2,159,156.8
XS GIS Cut Line= 2
     1528086.499      317853.608     1528660.849        318414.7
#Sta/Elev= 30
       0     740    29.4  726.16    58.8  710.19    68.5  706.59    78.3  704.94
   166.5   700.2     186   699.9   195.8  700.14   205.6  701.62   215.4  703.84
   244.8  709.12   254.6  713.52   264.4  720.89   293.8  745.19   303.6   751.8
   313.3   756.4   342.7   766.6   411.3  791.42   430.8  800.08   440.6  803.07
   489.6  811.75   509.2  814.54   528.8  815.73   558.1  815.13   607.1  815.69
   626.7  815.23   675.6  811.84   763.8  806.64   773.6  805.37   802.9     800
#Mann= 3 , 0 , 0
       0      .1       0   166.5    .045       0   195.8      .1       0
Bank Sta=166.5,195.8
XS Rating Curve= 0 ,0
Exp/Cntr=0.3,0.1

Type RM Length L Ch R = 1 ,44670.2 ,88.4,88.2,83.2
XS GIS Cut Line= 4
     1528096.295      317813.119     1528018.658      317989.183
     1528290.909      318264.267     1528162.727      318435.662
#Sta/Elev= 30
       0  747.37    38.5  743.42      77  733.22    96.2   727.1   115.4   718.9
   134.7  709.49   144.3  706.13   163.6  704.72   211.8  705.24   240.8  700.91
   260.2  699.31   269.8  699.21   288.1  699.53   424.6   701.8   463.3  703.66
   540.8  704.94   550.4  706.36   569.8  713.43   579.4   715.4   589.2  709.34
   598.9  706.91   608.6  705.81   628.1  706.57     667  710.47   676.7  714.02
   686.5  719.74   715.6   741.3   735.1  754.09   754.6  764.12   793.5  782.01
#Mann= 3 , 0 , 0
       0      .1       0   260.2    .045       0   288.1      .1       0
#XS Ineff= 2 , 0
                          578.03          715.74
Permanent Ineff=
       F       F
Bank Sta=260.2,288.1
XS Rating Curve= 0 ,0
Exp/Cntr=0.3,0.1

Type RM Length L Ch R = 1 ,44582   ,146.5,196.7,246.6
XS GIS Cut Line= 4
     1528026.851        317821.8     1527949.214      317997.863
     1528221.464      318272.948     1528093.283      318444.343
#Sta/Elev= 30
       0  750.02    67.4  730.32      77  726.34    86.6  721.38   105.8  710.14
   115.4  706.02   125.1  703.96   163.6  703.07   192.4  699.98   231.1  699.03
   262.2  699.77   279.5  700.87   318.2   705.3   327.9  705.78   356.9  704.16
   376.3  704.09   405.3  703.28   492.4  703.34   521.4  703.71   550.4  705.48
   579.4  707.89   598.9  707.99   608.6  710.56   618.4  715.51     667  749.99
   676.7  756.11   686.5  761.29   744.8  787.37   783.8  806.07   793.5  810.01
#Mann= 3 , 0 , 0
       0      .1       0   231.1    .045       0   262.2      .1       0
Bank Sta=231.1,262.2
XS Rating Curve= 0 ,0
Exp/Cntr=0.3,0.1

Type RM Length L Ch R = 1 ,44385.3 ,322.5,337.2,352.3
XS GIS Cut Line= 3
     1527983.344      317885.211     1527741.374      318015.419
     1527497.233      318068.588
#Sta/Elev= 30
       0  723.06     9.8  717.23    19.6  711.89    29.4  707.52    39.2  704.77
    49.1  703.56    68.7  702.51   127.6  698.61   147.2  697.73   166.8  697.36
   187.7  698.01   202.7  698.12   225.7  697.91   235.5  698.13   245.3  699.24
   255.2  702.04     265  705.59   274.8   708.7   284.4  712.39     294  717.94
     342  750.76   380.5  776.79   390.1  783.04   399.7  788.99   457.4  823.88
     467  828.79   476.6  832.88   505.4  844.39     515  848.19   524.6  850.51
#Mann= 3 , 0 , 0
       0      .1       0   187.7    .045       0   202.7      .1       0
Bank Sta=187.7,202.7
XS Rating Curve= 0 ,0
Exp/Cntr=0.3,0.1

Type RM Length L Ch R = 1 ,44048   ,327.5,322.1,316.6
XS GIS Cut Line= 2
     1528082.568      317719.759     1527676.586      317650.412
#Sta/Elev= 30
       0  754.99     9.8  754.16    39.2  750.95      49   749.5    58.8  746.25
    68.6  740.34    78.4     733    88.3  725.14    98.1  718.87   107.9  715.61
   117.7  713.05   127.5  709.77   137.3  707.14   147.1   705.8   156.9  705.04
   264.8  697.42   294.2  695.56   295.2  695.58     304  695.71   310.2  697.44
   313.8  698.44   323.6  703.73   333.4  707.68   343.2  709.89     353  712.64
   372.6  719.72   382.4  723.78   392.2  728.74   402.1  734.16   411.9     740
#Mann= 3 , 0 , 0
       0     .06       0   295.2    .045       0   310.2      .1       0
Bank Sta=295.2,310.2
XS Rating Curve= 0 ,0
Exp/Cntr=0.3,0.1