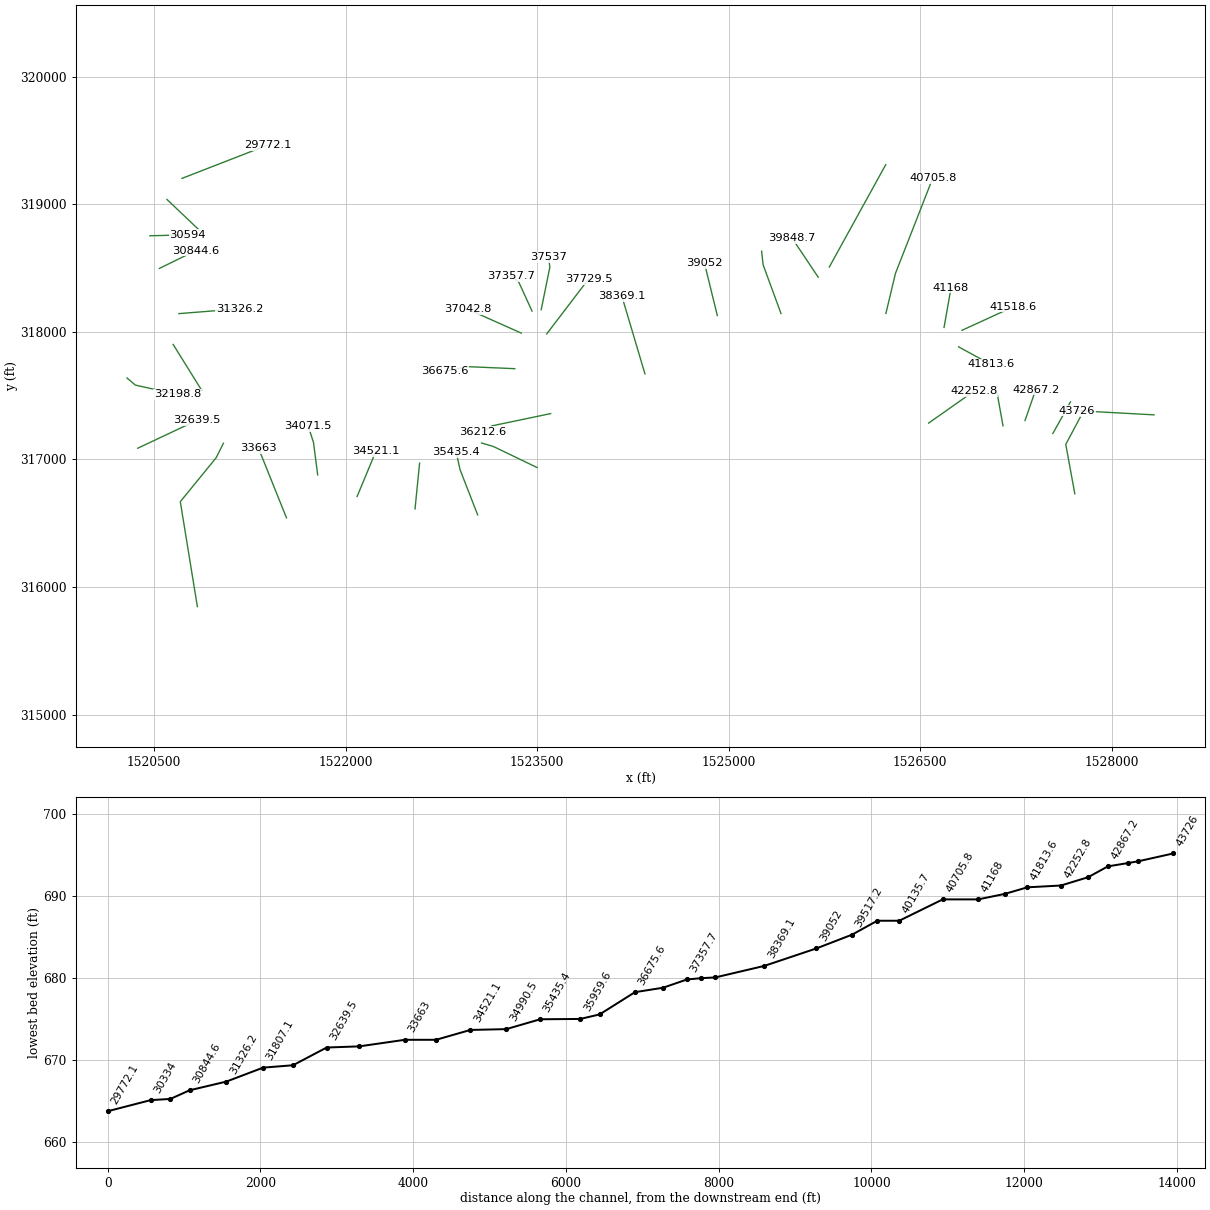
HEC-RAS study McKimCr.prj: McKimCr

--- McKimCr.g01 (geometry) --- (continued)

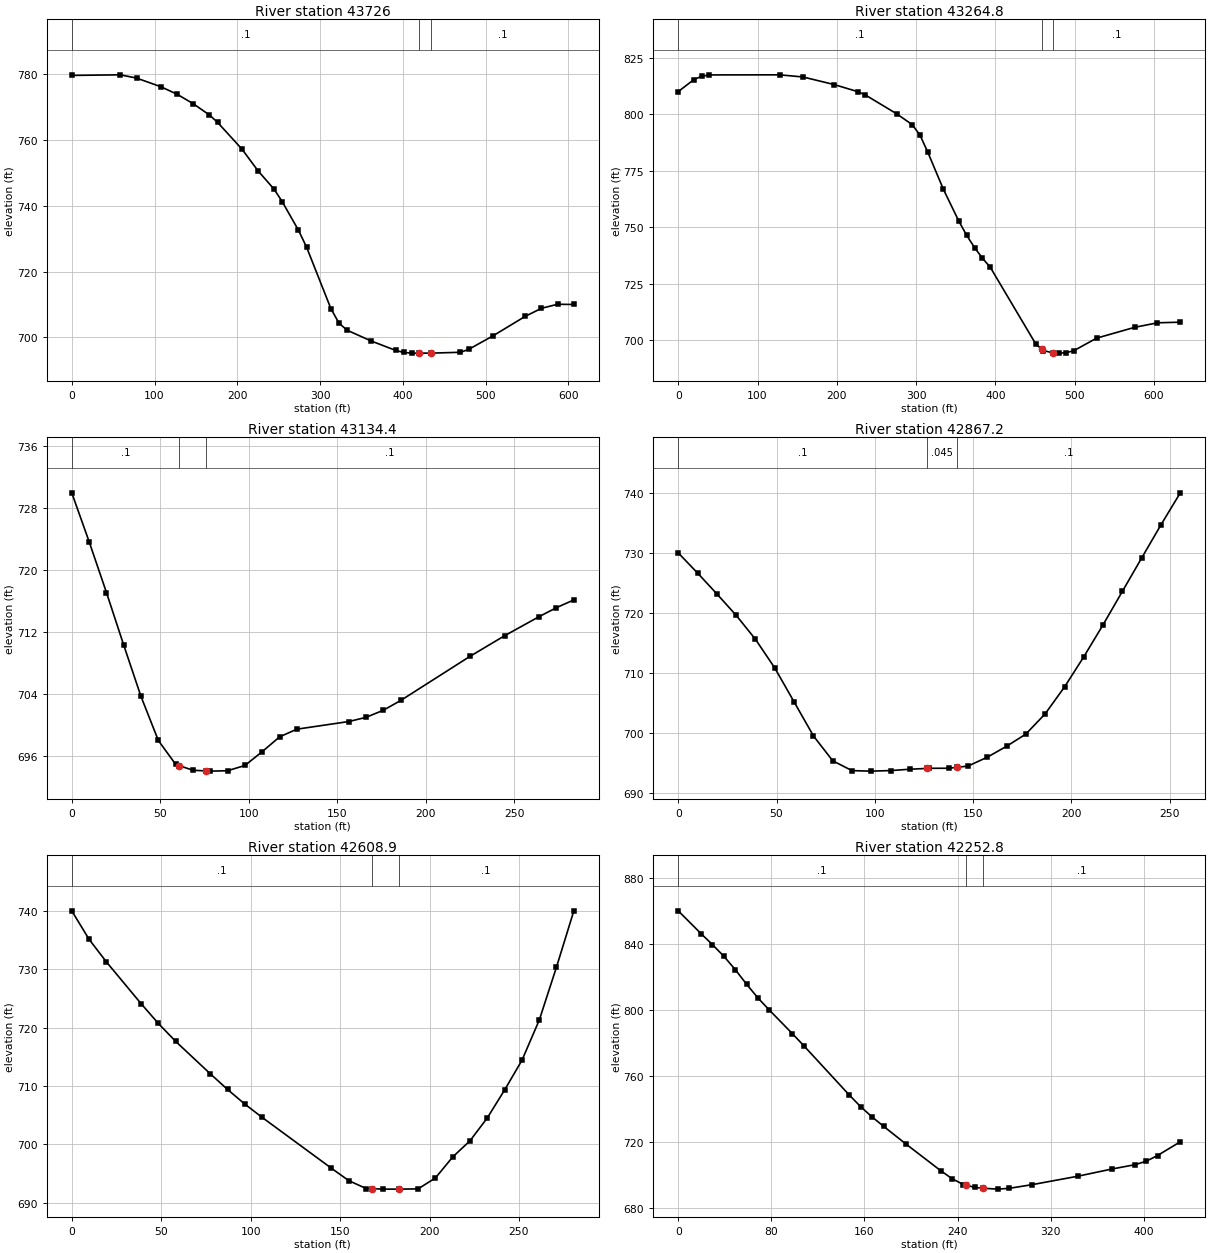
Type RM Length L Ch R = 1 ,43726   ,506.7,461.2,415.6
XS GIS Cut Line= 2
     1528331.505      317349.001     1527725.811       317381.98
#Sta/Elev= 30
       0   779.7    58.7  779.88    78.3  778.89   107.6  776.26   127.2  773.98
   146.8  771.08   166.3  767.66   176.1  765.43   205.5  757.31     225  750.68
   244.6  745.03   254.4  741.23   273.9  732.59   283.7  727.44   313.1  708.72
   322.9  704.31   332.6  702.18     362  698.87   391.4  696.02   401.1   695.4
   410.9   695.2   419.2   695.2   434.2   695.2   469.6  695.46   479.4  696.32
   508.8  700.44   547.9   706.4   567.5  708.84     587  710.07   606.6     710
#Mann= 3 , 0 , 0
       0      .1       0   419.2    .045       0   434.2      .1       0
Bank Sta=419.2,434.2
XS Rating Curve= 0 ,0
Exp/Cntr=0.3,0.1

Type RM Length L Ch R = 1 ,43264.8 ,130.9,130.4,130.1
XS GIS Cut Line= 3
     1527710.881      316730.292     1527639.996      317117.403
     1527752.707      317329.134
#Sta/Elev= 30
       0     810    19.7  815.31    29.5  816.79    39.4  817.39   127.9  817.43
   157.4  816.48   196.8  813.11   226.3     810   236.1  808.51   275.5  800.19
   295.2  795.38     305  790.73   314.8  783.21   334.5  766.76   354.2  752.51
     364  746.32   373.9   740.9   383.7  736.29   393.6  732.28   451.1  698.25
   458.3  696.08   460.7  695.35   473.3  694.34   479.9  694.24   489.5  694.42
   499.1  695.33   527.9  700.88   575.8  705.66   604.6  707.66   633.4  707.94
#Mann= 3 , 0 , 0
       0      .1       0   458.3    .045       0   473.3      .1       0
Bank Sta=458.3,473.3
XS Rating Curve= 0 ,0
Exp/Cntr=0.3,0.1

Type RM Length L Ch R = 1 ,43134.4 ,263,267.2,271.4
XS GIS Cut Line= 2
     1527538.804      317202.867     1527676.752      317450.662
#Sta/Elev= 25
       0     730     9.8  723.69    19.6  717.11    29.3  710.35    39.1  703.68
    48.9  697.99    58.7   694.9    60.7  694.74    68.5  694.14    75.7  694.06
    78.2  694.03      88  694.08    97.8  694.76   107.6  696.55   117.4  698.46
   127.1  699.45   156.5  700.44   166.2  700.98     176   701.9   185.8  703.16
   224.9  708.86   244.5  711.53     264     714   273.8  715.16   283.6  716.16
#Mann= 3 , 0 , 0
       0      .1       0    60.7    .045       0    75.7      .1       0
Bank Sta=60.7,75.7
XS Rating Curve= 0 ,0
Exp/Cntr=0.3,0.1

Type RM Length L Ch R = 1 ,42867.2 ,246.9,258.4,269.7
XS GIS Cut Line= 2
      1527320.74      317304.385     1527404.531      317545.656
#Sta/Elev= 29
       0     730     9.8  726.65    19.6  723.18    29.5  719.58    39.3  715.59
    49.1  710.82    58.9  705.18    68.8  699.48    78.6  695.34    88.4   693.7
    98.2  693.62   108.1  693.71   117.9  693.94   126.6  694.07   127.7  694.09
   137.5   694.1   141.6  694.25   147.4  694.46   157.2  695.94     167  697.76
   176.8  699.79   186.6  703.15   196.5  707.65   206.3  712.68   216.1  718.01
   225.9  723.57   235.8  729.18   245.6   734.7   255.4  740.01
#Mann= 3 , 0 , 0
       0      .1       0   126.6    .045       0   141.6      .1       0
Bank Sta=126.6,141.6
XS Rating Curve= 0 ,0
Exp/Cntr=0.3,0.1

Type RM Length L Ch R = 1 ,42608.9 ,382,356.1,330.1
XS GIS Cut Line= 2
      1527148.42      317263.227     1527098.553      317539.471
#Sta/Elev= 26
       0  739.99     9.7  735.11    19.4  731.23    38.7  724.11    48.4   720.7
    58.1  717.62    77.4  712.08    87.1  709.38    96.8  706.86   106.5  704.58
   145.2  695.87   154.9  693.75   164.6   692.4   167.7  692.37   174.2   692.3
   182.7   692.3   193.6  692.34   203.3  694.21     213  697.82   222.6  700.57
   232.3   704.5     242   709.3   251.7  714.39   261.4   721.3     271  730.36
   280.7     740
#Mann= 3 , 0 , 0
       0      .1       0   167.7    .045       0   182.7      .1       0
Bank Sta=167.7,182.7
XS Rating Curve= 0 ,0
Exp/Cntr=0.3,0.1

Type RM Length L Ch R = 1 ,42252.8 ,465.5,439.2,412.8
XS GIS Cut Line= 2
      1526566.03      317284.593     1526918.726      317532.987
#Sta/Elev= 30
       0     860    19.6  846.17    29.4  839.51    39.2  832.45      49  824.36
    58.8  815.43    68.6  807.09    78.4  799.76      98  785.59   107.8   778.3
   147.1  748.23   156.9  741.16   166.7  734.96   176.5  729.34   196.1  718.39
   225.5  702.49   235.3  697.61   245.1  694.04   246.9  693.73   254.9  692.33
   261.9  691.82   274.5  691.29   284.3  691.76   303.9  693.98   343.2  699.09
   372.6  703.48   392.2  706.07     402  708.16   411.8  711.66   431.4     720
#Mann= 3 , 0 , 0
       0      .1       0   246.9    .045       0   261.9      .1       0
Bank Sta=246.9,261.9
XS Rating Curve= 0 ,0
Exp/Cntr=0.3,0.1

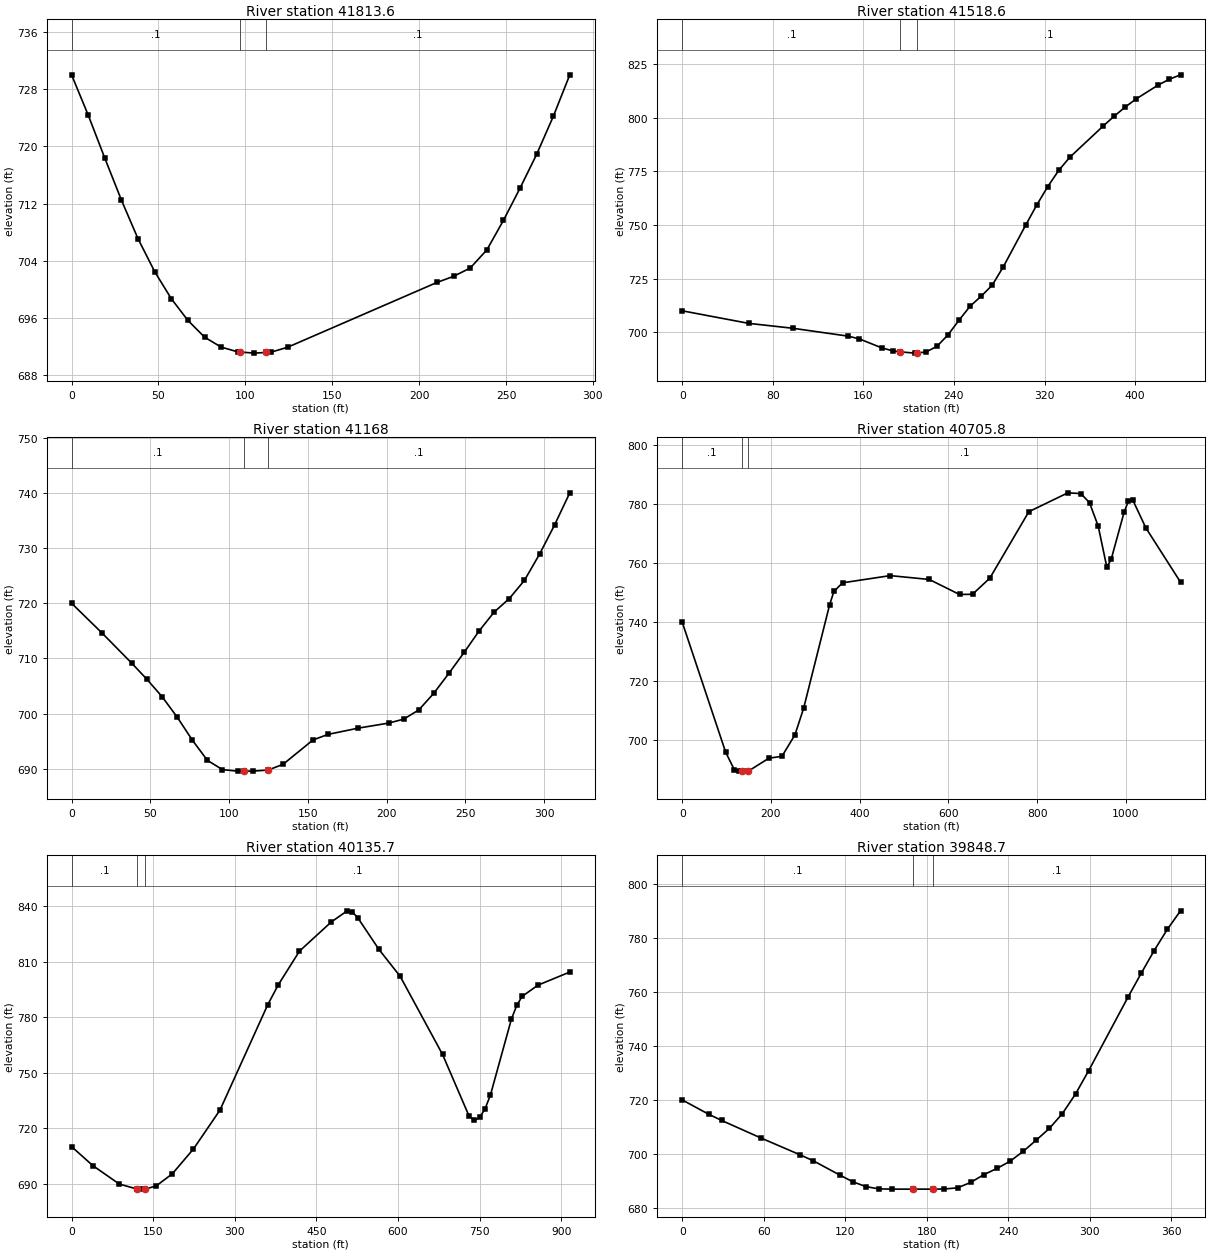
Type RM Length L Ch R = 1 ,41813.6 ,273.6,295,316.5
XS GIS Cut Line= 2
     1526800.616      317881.863     1527052.465       317744.77
#Sta/Elev= 25
       0     730     9.6  724.35    19.1  718.36    28.7  712.46    38.2  707.09
    47.8  702.48    57.4  698.68    66.9  695.66    76.5  693.31      86  691.92
    95.6  691.25    96.7  691.23   105.1  691.07   111.7  691.16   114.7   691.2
   124.3  691.89   210.3  700.96   219.8  701.81   229.4  702.97     239  705.52
   248.5  709.63   258.1  714.16   267.6  718.86   277.2  724.18   286.7     730
#Mann= 3 , 0 , 0
       0      .1       0    96.7    .045       0   111.7      .1       0
Bank Sta=96.7,111.7
XS Rating Curve= 0 ,0
Exp/Cntr=0.3,0.1

Type RM Length L Ch R = 1 ,41518.6 ,327.9,350.5,373.2
XS GIS Cut Line= 2
     1526827.246      318011.674     1527227.261      318195.155
#Sta/Elev= 30
       0  709.99    58.7  704.14    97.8  701.85   146.7  698.17   156.5  696.88
     176  692.76   185.8  691.34   192.5  690.86   205.4  690.27   207.5  690.38
   215.2  690.78   224.9   693.4   234.7  698.77   244.5  705.66   254.3  712.18
     264  716.79   273.8  721.96   283.6  730.54   303.2  749.81     313  759.21
   322.7  767.78   332.5  775.44   342.3  781.57   371.6  796.03   381.4  800.67
   391.2  804.95     401   808.8   420.5  815.27   430.3  817.96   440.1     820
#Mann= 3 , 0 , 0
       0      .1       0   192.5    .045       0   207.5      .1       0
Bank Sta=192.5,207.5
XS Rating Curve= 0 ,0
Exp/Cntr=0.3,0.1

Type RM Length L Ch R = 1 ,41168   ,463.6,462.2,460.9
XS GIS Cut Line= 2
     1526686.718      318034.257     1526741.561      318345.729
#Sta/Elev= 30
       0     720    19.2  714.65    38.3  709.12    47.9  706.21    57.5  703.07
    67.1  699.36    76.7   695.2    86.2  691.56    95.8  689.87   105.4   689.6
   109.7   689.6     115   689.6   124.7  689.79   134.2  690.82   153.3  695.25
   162.9  696.26   182.1  697.39   201.3   698.3   210.8  699.01   220.4  700.67
     230  703.71   239.6  707.33   249.2  711.09   258.8  715.01   268.3  718.41
   277.9  720.85   287.5  724.14   297.1  728.89   306.7  734.21   316.3     740
#Mann= 3 , 0 , 0
       0      .1       0   109.7    .045       0   124.7      .1       0
Bank Sta=109.7,124.7
XS Rating Curve= 0 ,0
Exp/Cntr=0.3,0.1

Type RM Length L Ch R = 1 ,40705.8 ,576.5,570,563.5
XS GIS Cut Line= 3
     1526231.217      318143.992     1526306.033      318457.485
      1526597.71       319203.57
#Sta/Elev= 30
       0     740    97.7  696.04   117.2   690.1     127   689.6   133.9   689.6
   148.9   689.6   195.3  693.99   224.6  694.61   253.9  701.86   273.5  710.86
   332.1  745.92   341.8  750.49   361.4  753.42   468.8  755.86   556.8  754.56
   625.1  749.47   654.4  749.54   693.5  755.01   781.4  777.52   869.4  783.92
   898.7  783.66   918.2  780.58   937.8  772.65   957.3   758.7   967.1   761.4
   996.4  777.45  1006.1  781.18  1015.9  781.44  1045.2  772.06  1123.4  753.65
#Mann= 3 , 0 , 0
       0      .1       0   133.9    .045       0   148.9      .1       0
Bank Sta=133.9,148.9
XS Rating Curve= 0 ,0
Exp/Cntr=0.3,0.1

Type RM Length L Ch R = 1 ,40135.7 ,261.8,287,312.2
XS GIS Cut Line= 2
     1525787.862      318507.722     1526229.872      319309.907
#Sta/Elev= 30
       0     710      39  699.74    87.7  689.75   120.7  687.01   126.7     687
   135.7  687.01   155.9  688.81   185.1  695.25   224.1  708.74   272.8  729.75
   360.5  786.68     380  797.52     419  815.78   477.4  831.52   506.7  837.56
   516.4  836.88   526.2  833.78   565.1  816.66   604.1  802.11     682  759.85
   730.8  726.49   740.5  724.13   750.3   725.8     760  730.38   769.8  737.68
   808.7   779.1   818.5  786.43   828.2  791.25   857.4  797.35   915.9  804.44
#Mann= 3 , 0 , 0
       0      .1       0   120.7    .045       0   135.7      .1       0
Bank Sta=120.7,135.7
XS Rating Curve= 0 ,0
Exp/Cntr=0.3,0.1

Type RM Length L Ch R = 1 ,39848.7 ,336.9,331.5,326.2
XS GIS Cut Line= 2
     1525701.197      318427.957     1525497.323      318733.075
#Sta/Elev= 30
       0     720    19.3  714.75      29  712.41    57.9  705.93    86.9  699.67
    96.6  697.46   115.9  692.24   125.5  689.74   135.2  687.94   144.8  687.09
   154.5     687   169.7     687   184.7     687   193.1  687.04   202.8  687.49
   212.4  689.47   222.1  692.35   231.8  694.66   241.4   697.3   251.1  700.96
   260.7  705.12   270.4  709.47     280  714.96   289.7  722.23   299.4   730.9
   328.3  758.03     338  766.84   347.6  775.29   357.3  783.15     367     790
#Mann= 3 , 0 , 0
       0      .1       0   169.7    .045       0   184.7      .1       0
Bank Sta=169.7,184.7
XS Rating Curve= 0 ,0
Exp/Cntr=0.3,0.1

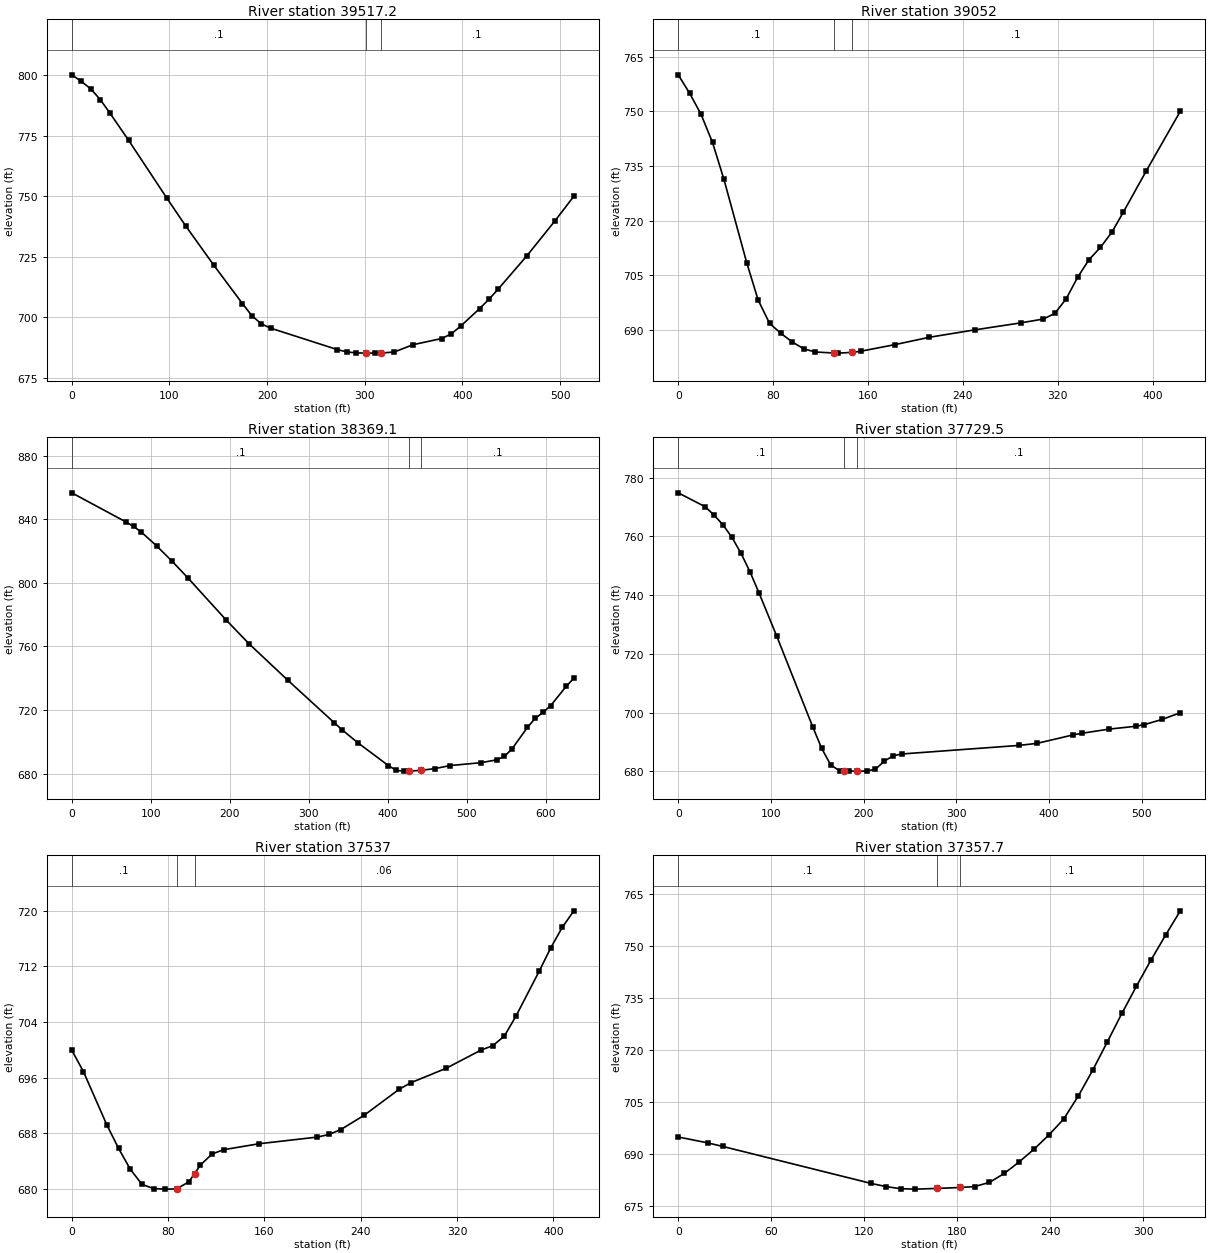
Type RM Length L Ch R = 1 ,39517.2 ,467.6,465.1,462.7
XS GIS Cut Line= 3
     1525409.559      318143.457     1525269.223      318526.382
     1525257.951      318632.044
#Sta/Elev= 30
       0  800.05     9.7  797.37    19.4  794.29    29.1  789.87    38.8  784.43
    58.3     773    97.1  749.36   116.5  737.83   145.6  721.46   174.8   705.7
   184.5  700.69   194.2  697.34   203.9  695.56   271.9  686.76   281.6   685.8
   291.3   685.4   301.2  685.31   310.7   685.3   316.2  685.31   330.2  685.77
   349.6   688.8   378.7  691.31   388.4  693.19   398.1  696.37   417.5  703.63
   427.2  707.51   436.8  711.78   465.8  725.33   494.8  739.84   514.1  749.99
#Mann= 3 , 0 , 0
       0      .1       0   301.2    .045       0   316.2      .1       0
Bank Sta=301.2,316.2
XS Rating Curve= 0 ,0
Exp/Cntr=0.3,0.1

Type RM Length L Ch R = 1 ,39052   ,681.8,682.9,684.1
XS GIS Cut Line= 2
     1524910.856      318127.513     1524809.992      318538.664
#Sta/Elev= 30
       0     760     9.6  754.95    19.2  749.18    28.9  741.44    38.5  731.35
    57.7  708.49    67.4  698.18      77   691.8    86.6  689.03    96.2  686.68
   105.8  684.81   115.5  683.94   131.5  683.66   134.7  683.63   146.5  683.83
   153.9  684.15   182.8  685.97   211.7  687.98   250.2  690.02   288.6  691.92
   307.9  692.99   317.5  694.53   327.1  698.55   336.8  704.48   346.4  709.31
     356  712.66   365.6  716.82   375.2  722.28   394.5  733.58   423.3     750
#Mann= 3 , 0 , 0
       0      .1       0   131.5    .045       0   146.5      .1       0
Bank Sta=131.5,146.5
XS Rating Curve= 0 ,0
Exp/Cntr=0.3,0.1

Type RM Length L Ch R = 1 ,38369.1 ,660.7,639.5,618.4
XS GIS Cut Line= 2
     1524344.005      317670.614     1524163.114       318280.03
#Sta/Elev= 30
       0  856.78    68.5  838.47    78.2  835.64      88  832.09   107.6  823.28
   127.1  813.67   146.7  803.36   195.6  776.61   224.9  761.49   273.8  738.63
   332.5   711.9   342.3  707.51   361.9  699.48     401  684.95   410.8  681.97
   420.5   681.5     427   681.5     442  682.01   459.7  683.08   479.2  685.02
   518.3  686.82   537.9   688.6   547.7  690.72   557.5  695.54     577   709.1
   586.8  714.77   596.6  718.45   606.4  722.78   625.9  734.82   635.7  740.01
#Mann= 3 , 0 , 0
       0      .1       0     427    .045       0     442      .1       0
Bank Sta=427,442
XS Rating Curve= 0 ,0
Exp/Cntr=0.3,0.1

Type RM Length L Ch R = 1 ,37729.5 ,181.2,192.6,203.7
XS GIS Cut Line= 2
     1523574.474      317983.114     1523902.817      318414.012
#Sta/Elev= 30
       0  774.82      29  770.09    38.7  767.24    48.4  763.89      58  759.62
    67.7  754.26    77.4  747.94    87.1  740.79   106.4  725.94   145.1  695.18
   154.8  687.82   164.5   682.2   174.1  680.21   178.4  680.16   183.8   680.1
   193.4   680.1   203.2  680.13   212.8  680.76   222.5  683.52   232.2  685.38
   241.8  685.95   367.6  688.85     387  689.54   425.6   692.4   435.3  692.97
   464.4  694.38   493.4  695.36     503  695.94   522.4  697.72   541.7  699.99
#Mann= 3 , 0 , 0
       0      .1       0   178.4    .045       0   193.4      .1       0
Bank Sta=178.4,193.4
XS Rating Curve= 0 ,0
Exp/Cntr=0.3,0.1

Type RM Length L Ch R = 1 ,37537   ,165.5,179.3,193.3
XS GIS Cut Line= 3
     1523531.504      318173.454     1523599.252      318506.697
     1523589.582      318583.058
#Sta/Elev= 30
       0  699.97     9.7  696.88    29.2   689.2    38.9  685.84    48.6  682.86
    58.3  680.68      68  680.08    77.7     680      87  680.03    97.2  681.04
     102  682.24   106.9  683.47   116.6  685.06   126.3  685.67   155.5  686.52
     204  687.48   213.8  687.86   223.5  688.56   242.9  690.62     272  694.36
   281.8   695.3   310.9  697.36   340.1     700   349.7  700.61   359.3     702
   368.9  704.85   388.2  711.31   397.8  714.66   407.4  717.62     417  719.99
#Mann= 3 , 0 , 0
       0      .1       0      87    .045       0     102     .06       0
Bank Sta=87,102
XS Rating Curve= 0 ,0
Exp/Cntr=0.3,0.1

Type RM Length L Ch R = 1 ,37357.7 ,298.1,314.9,331.6
XS GIS Cut Line= 3
     1523459.629      318162.468     1523356.397      318388.587
      1523298.16      318436.325
#Sta/Elev= 24
       0  694.87    19.1  693.16    28.7  692.15   124.3  681.51   133.8   680.6
   143.4  679.97     153  679.85   166.8  680.05   181.8  680.32   191.2  680.58
   200.8   681.8   210.3  684.36   219.9  687.67   229.4   691.3     239   695.4
   248.6     700     258   706.6   267.4  714.12   276.8  722.24   286.2  730.47
   295.6   738.3     305  745.85   314.5  753.09   323.9  760.01
#Mann= 3 , 0 , 0
       0      .1       0   166.8    .045       0   181.8      .1       0
Bank Sta=166.8,181.8
XS Rating Curve= 0 ,0
Exp/Cntr=0.3,0.1

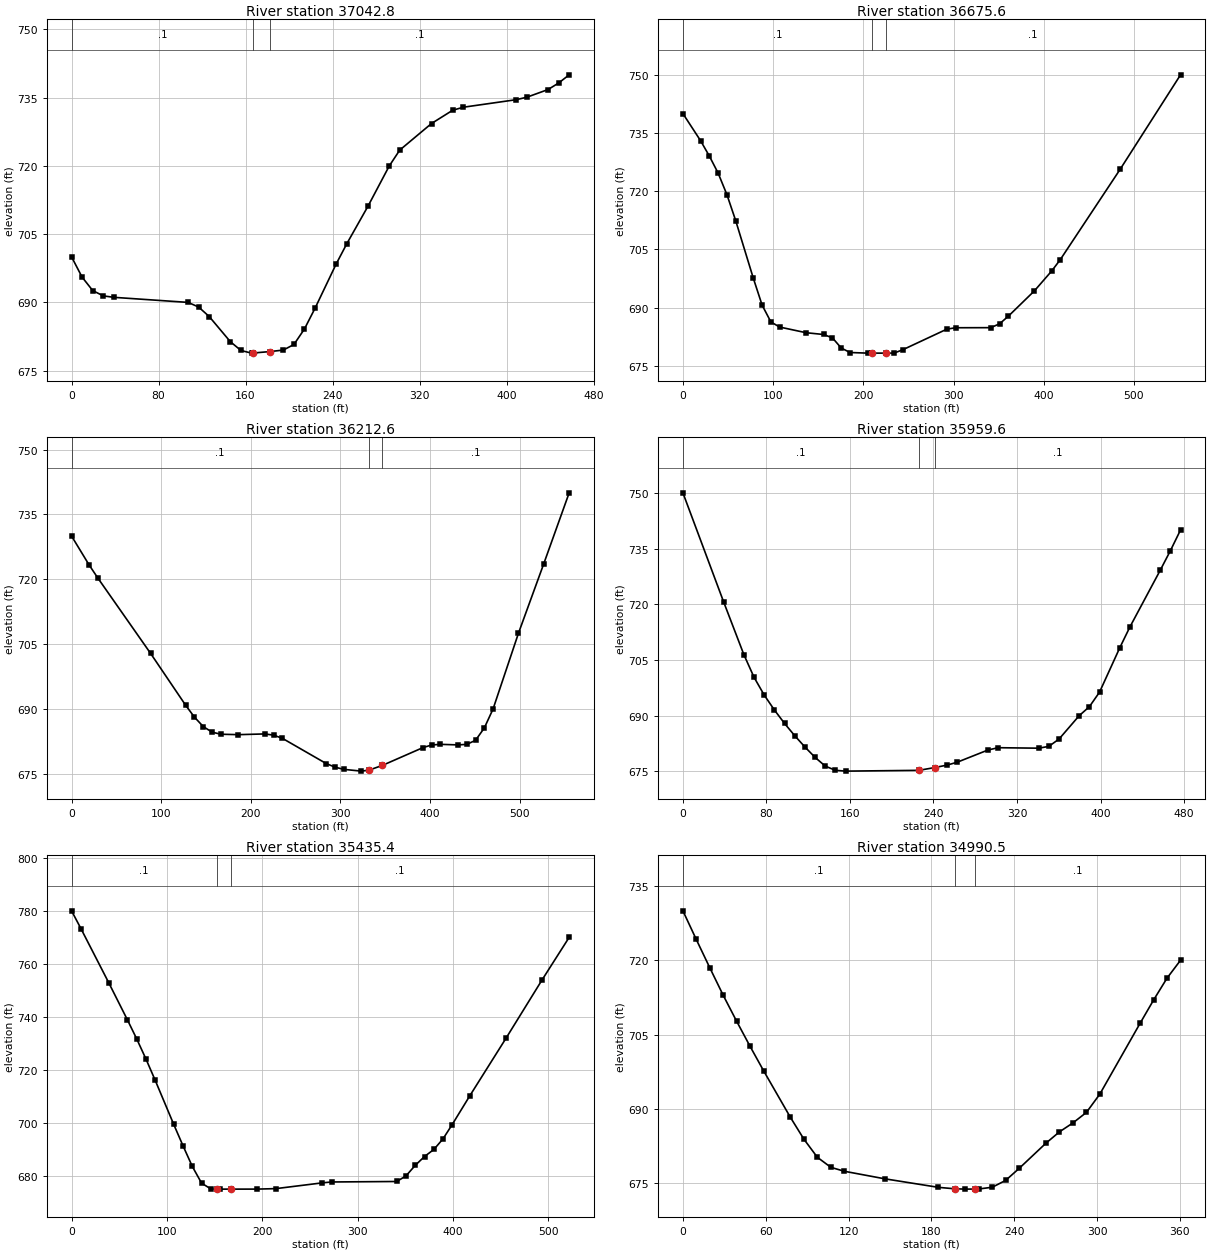
Type RM Length L Ch R = 1 ,37042.8 ,359.1,367.2,375.9
XS GIS Cut Line= 2
     1523375.426      317989.735     1522957.626      318176.468
#Sta/Elev= 30
       0     700     9.7  695.54    19.5  692.58    29.2  691.42      39   691.1
   107.1  689.99   116.8  688.98   126.6  686.88     146  681.36   155.8  679.42
   165.5  678.84   167.3  678.87   182.3  679.18   194.7  679.51   204.5  680.74
   214.2  684.16     224  688.75   243.4  698.46   253.2  702.92   272.6  711.13
   292.1  719.95   301.8  723.46     331   729.3   350.5  732.22   360.3  732.88
     409  734.54   418.7  735.08   438.2  736.77   447.9   738.2   457.6     740
#Mann= 3 , 0 , 0
       0      .1       0   167.3    .045       0   182.3      .1       0
Bank Sta=167.3,182.3
XS Rating Curve= 0 ,0
Exp/Cntr=0.3,0.1

Type RM Length L Ch R = 1 ,36675.6 ,456.8,463,468.7
XS GIS Cut Line= 3
     1523324.642      317711.026     1522954.475      317726.863
     1522777.272       317689.77
#Sta/Elev= 30
       0  740.01    19.5  733.06    29.2  729.12      39   724.7    48.8  719.12
    58.5  712.44      78  697.63    87.8  690.66    97.5  686.34   107.2  685.02
   136.5  683.56     156   683.1   165.8  682.22   175.5  679.62   185.2  678.46
   204.8   678.3   209.8   678.3   224.8   678.3     234   678.3   243.8  679.18
   292.5  684.47   302.2  684.84   341.2  684.86     351  685.85   360.8  687.83
   389.6  694.34   408.6  699.41   418.2  702.35   484.8  725.71   551.6     750
#Mann= 3 , 0 , 0
       0      .1       0   209.8    .045       0   224.8      .1       0
Bank Sta=209.8,224.8
XS Rating Curve= 0 ,0
Exp/Cntr=0.3,0.1

Type RM Length L Ch R = 1 ,36212.6 ,270.3,253.1,238
XS GIS Cut Line= 3
      1523605.53      317358.852     1523145.067       317262.56
     1523073.264       317217.33
#Sta/Elev= 30
       0     730    19.6  723.31    29.4  720.26    88.2  702.84   127.4  690.81
   137.2  688.07     147   685.9   156.8  684.61   166.6  684.13   186.2  684.03
   215.6   684.2   225.4  683.92   235.2  683.19   284.2  677.34     294  676.51
   303.8     676   323.4  675.59   331.8  675.81   346.8  676.91     392  681.02
   401.8  681.64   411.6  681.79   431.2  681.66     441  681.78   450.8  682.72
   460.6  685.58   470.4  689.99   498.7   707.5     527  723.62   555.3     740
#Mann= 3 , 0 , 0
       0      .1       0   331.8    .045       0   346.8      .1       0
Bank Sta=331.8,346.8
XS Rating Curve= 0 ,0
Exp/Cntr=0.3,0.1

Type RM Length L Ch R = 1 ,35959.6 ,539.3,524.2,506.9
XS GIS Cut Line= 3
     1523499.029      316936.246     1523157.041       317101.07
     1523064.069      317128.747
#Sta/Elev= 30
       0     750    38.9   720.7    58.4  706.41    68.1  700.33    77.9  695.51
    87.6  691.52    97.3   687.9   107.1  684.58   116.8  681.56   126.6  678.74
   136.3   676.4     146  675.26   155.8  675.04     226  675.25     241  675.99
   253.1  676.67   262.8  677.45     292  680.71   301.8  681.35   340.7  681.22
   350.4   681.7   360.2  683.67   379.6  689.99   389.3   692.4     399   696.3
   418.4  708.26   428.1  713.87   457.2  729.17   466.9  734.42   476.6     740
#Mann= 3 , 0 , 0
       0      .1       0     226    .045       0     241      .1       0
Bank Sta=226,241
XS Rating Curve= 0 ,0
Exp/Cntr=0.3,0.1

Type RM Length L Ch R = 1 ,35435.4 ,455.5,444.9,434.2
XS GIS Cut Line= 3
     1523033.755      316564.908     1522896.029      316919.169
     1522865.671      317057.795
#Sta/Elev= 30
       0     780     9.8  773.33      39  752.88    58.5  738.94    68.2   731.8
      78  724.14    87.7   716.1   107.2  699.41     117  691.29   126.7  683.54
   136.4  677.26   146.2  675.06   152.1  675.02   155.9     675   167.1     675
   194.9  675.01   214.4  675.19   263.1  677.37   272.9   677.7   341.1  677.88
   350.8  679.98   360.6     684   370.3  687.31   380.1  689.98   389.6  693.94
     399  699.19   417.9  710.29   455.8  731.96   493.6  753.96     522     770
#Mann= 3 , 0 , 0
       0      .1       0   152.1    .045       0   167.1      .1       0
Bank Sta=152.1,167.1
XS Rating Curve= 0 ,0
Exp/Cntr=0.3,0.1

Type RM Length L Ch R = 1 ,34990.5 ,475.7,469.4,460.7
XS GIS Cut Line= 2
     1522543.339      316611.621     1522579.141       316970.31
#Sta/Elev= 30
       0     730     9.7  724.21    19.5  718.49    29.2  712.94      39  707.66
    48.7  702.61    58.4  697.73    77.9  688.28    87.7  683.87    97.4  680.23
   107.2   678.2   116.9  677.41   146.1  675.89   185.1  674.16   196.8  673.87
   204.6   673.8   211.8  673.82   214.3  673.83   224.1  674.18   233.8  675.56
   243.6  677.99     263  683.08   272.8  685.37   282.5  687.16   292.3  689.29
     302  692.97   331.2  707.29     341     712   350.7   716.4   360.5  720.02
#Mann= 3 , 0 , 0
       0      .1       0   196.8    .045       0   211.8      .1       0
Bank Sta=196.8,211.8
XS Rating Curve= 0 ,0
Exp/Cntr=0.3,0.1

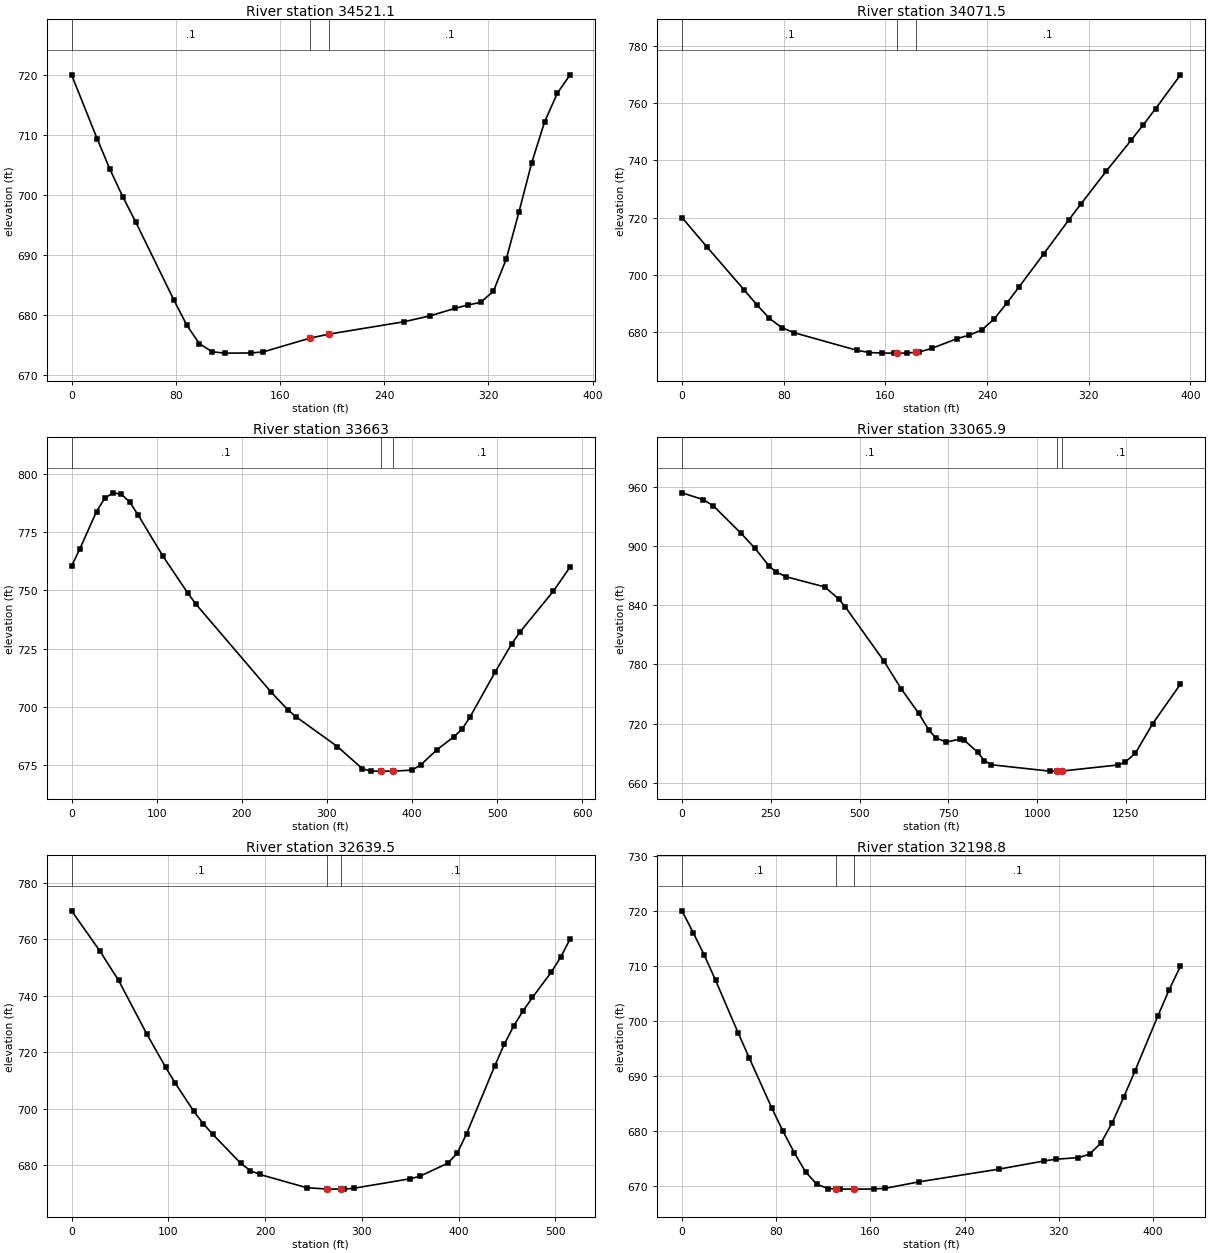
Type RM Length L Ch R = 1 ,34521.1 ,437.4,449.6,461
XS GIS Cut Line= 2
     1522089.667      316709.128     1522236.441      317062.595
#Sta/Elev= 26
       0     720    19.6  709.39    29.4   704.3    39.2  699.76    49.1  695.58
    78.5  682.56    88.3  678.41    98.1  675.27     108  673.92   117.8   673.7
   137.4  673.72   147.2  673.91     183  676.19     198  676.88   255.2  678.92
   274.8  679.88   294.4  681.15   304.2  681.71     314  682.14   323.8  683.98
   333.7  689.34   343.5  697.22   353.3   705.4   363.1  712.16   372.9  716.94
   382.7  720.01
#Mann= 3 , 0 , 0
       0      .1       0     183    .045       0     198      .1       0
Bank Sta=183,198
XS Rating Curve= 0 ,0
Exp/Cntr=0.3,0.1

Type RM Length L Ch R = 1 ,34071.5 ,403.5,408.5,414.2
XS GIS Cut Line= 3
     1521780.941      316878.518     1521748.224      317131.937
     1521706.602      317262.141
#Sta/Elev= 30
       0     720    19.7  709.65    49.1  694.54      59  689.38    68.8  684.65
    78.6  681.41    88.4  679.62   137.6  673.49   147.4  672.71   157.2  672.52
   167.1   672.5   169.1   672.5   176.9  672.51   184.1  672.82   186.7  672.93
   196.6  674.16   216.2  677.55     226  678.81   235.9   680.6   245.7  684.52
   255.5     690   265.3  695.76   284.8   707.4   304.3  719.14   314.1  724.89
   333.6  736.15   353.2     747   362.9  752.47   372.7   758.2   392.2     770
#Mann= 3 , 0 , 0
       0      .1       0   169.1    .045       0   184.1      .1       0
Bank Sta=169.1,184.1
XS Rating Curve= 0 ,0
Exp/Cntr=0.3,0.1

Type RM Length L Ch R = 1 ,33663   ,622.2,597.1,571.7
XS GIS Cut Line= 2
     1521536.452      316541.808     1521318.344      317085.339
#Sta/Elev= 30
       0  760.44     9.8  767.91    29.3  783.83      39  789.55    48.8  791.85
    58.6   791.2    68.3  787.87    78.1  782.38   107.4  764.65   136.6  748.82
   146.4  743.97   234.3  706.43   253.8  698.92   263.6  695.83   312.4  683.01
   341.6  673.56   351.4   672.5   363.1   672.5   378.1   672.5   400.2  672.94
     410  675.12   429.5  681.73     449  687.19   458.8  690.48   468.5  695.92
   497.8  715.07   517.3  727.17   527.1  732.29   566.1  749.68   585.7     760
#Mann= 3 , 0 , 0
       0      .1       0   363.1    .045       0   378.1      .1       0
Bank Sta=363.1,378.1
XS Rating Curve= 0 ,0
Exp/Cntr=0.3,0.1

Type RM Length L Ch R = 1 ,33065.9 ,436.8,426.4,416
XS GIS Cut Line= 4
     1520838.536      315846.495      1520704.91       316668.43
     1520985.791       317012.73     1521042.754      317126.256
#Sta/Elev= 30
       0  954.09    58.8   947.3    88.2  940.91   166.6  912.94   205.7  897.74
   244.9  879.97   264.5  873.84   293.9  868.87   401.7  858.63   440.9  846.58
   460.4  838.12   568.2  783.66   617.2  755.37   666.2  730.58   695.6  713.23
   715.2  705.35   744.6  701.17   783.7   704.3   793.5  703.56   832.7  690.82
     852  682.24   871.4  678.17  1035.6   671.7  1055.3   671.7  1070.3  671.78
  1228.8  677.98  1248.1  680.78  1277.1  689.93  1325.9  719.93  1404.1     760
#Mann= 3 , 0 , 0
       0      .1       0  1055.3    .045       0  1070.3      .1       0
Bank Sta=1055.3,1070.3
XS Rating Curve= 0 ,0
Exp/Cntr=0.3,0.1

Type RM Length L Ch R = 1 ,32639.5 ,455.8,440.7,425.6
XS GIS Cut Line= 2
      1520371.31      317087.224     1520837.253      317307.104
#Sta/Elev= 30
       0     770    29.2   755.8    48.6  745.38    77.8  726.39    97.2  714.66
   106.9  709.16   126.4  699.05   136.1   694.7   145.8  690.98     175  680.64
   184.7  678.12   194.4  676.76     243  672.07   263.9  671.59   278.9  671.57
   281.9  671.56   291.6  671.86     350  675.23   359.7  676.08   388.8  680.72
   398.6  684.29   408.3  691.19   437.4  715.19   447.2  722.79   456.9  729.24
   466.6   734.6   476.3  739.36   495.8   748.3   505.5   753.6   515.2  759.99
#Mann= 3 , 0 , 0
       0      .1       0   263.9    .045       0   278.9      .1       0
Bank Sta=263.9,278.9
XS Rating Curve= 0 ,0
Exp/Cntr=0.3,0.1

Type RM Length L Ch R = 1 ,32198.8 ,410.6,391.7,372.7
XS GIS Cut Line= 3
     1520287.595      317637.843     1520352.869      317582.412
      1520682.39      317508.796
#Sta/Elev= 30
       0  720.01     9.5  716.04      19  711.92    28.5  707.37    47.6  697.85
    57.1  693.25    76.1  684.22    85.6  679.99    95.3  676.04   104.9  672.53
   114.6  670.26   124.2   669.5   131.1  669.43   133.9   669.4   146.1   669.4
   162.8  669.42   172.5  669.55   201.4  670.73   268.9  673.03   307.5  674.52
   317.2  674.83   336.5  675.13   346.1  675.75   355.8   677.8   365.4  681.51
     375  686.08   384.7  690.92     404  700.85   413.6  705.62   423.3  709.97
#Mann= 3 , 0 , 0
       0      .1       0   131.1    .045       0   146.1      .1       0
Bank Sta=131.1,146.1
XS Rating Curve= 0 ,0
Exp/Cntr=0.3,0.1

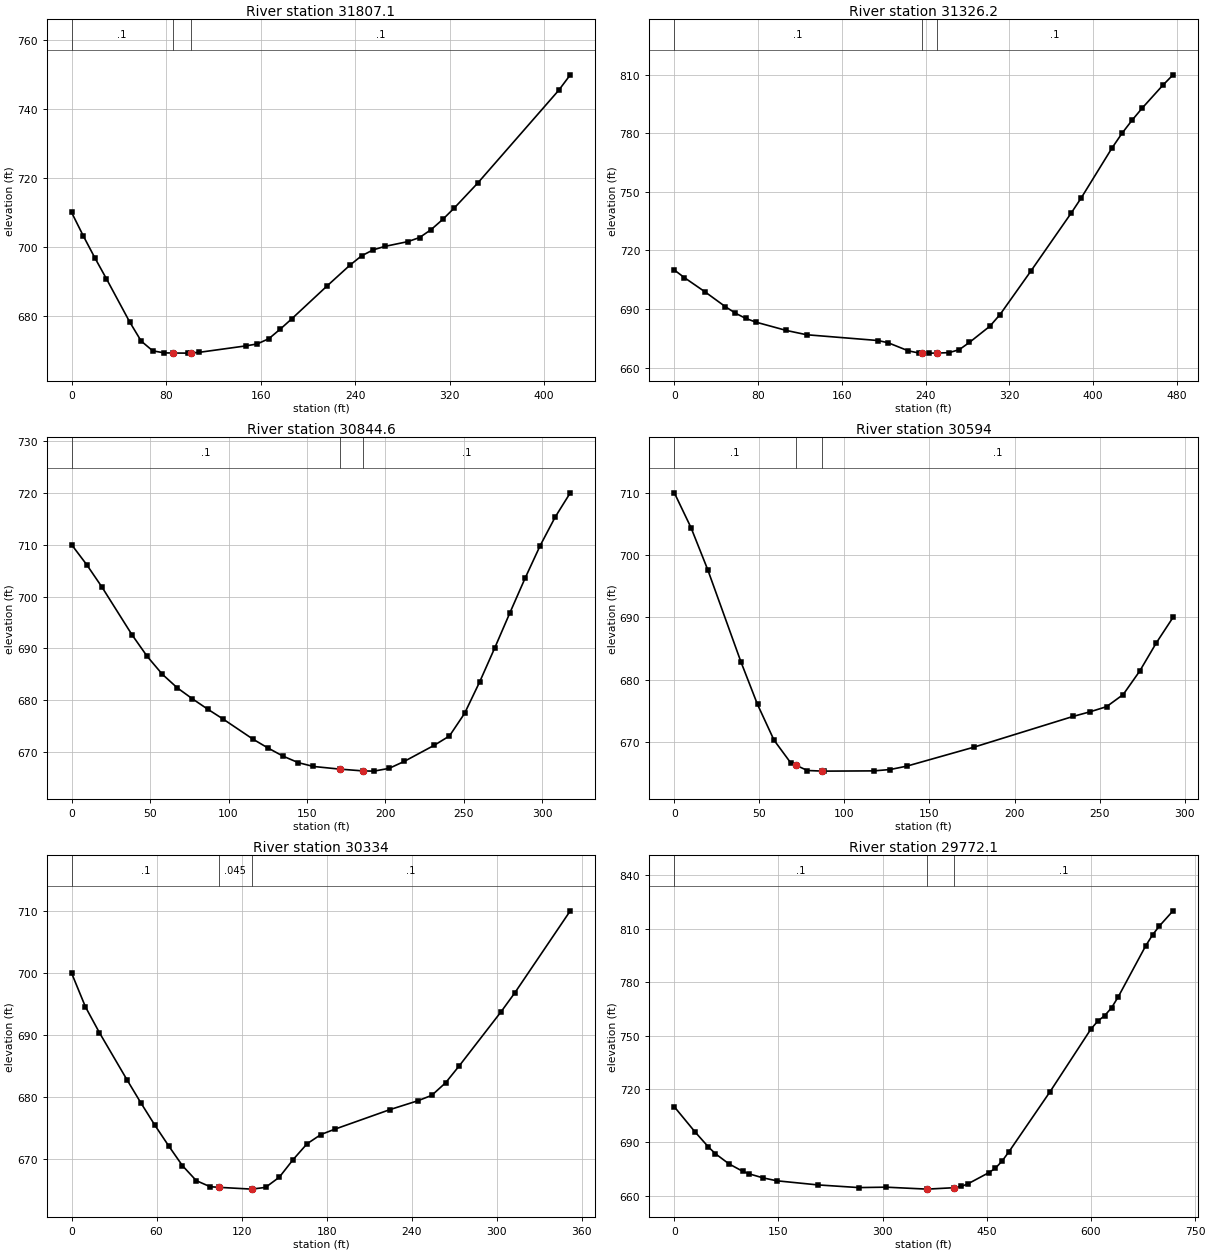
Type RM Length L Ch R = 1 ,31807.1 ,456.1,480.9,505.6
XS GIS Cut Line= 2
     1520649.054        317900.5     1520872.026      317542.132
#Sta/Elev= 30
       0     710     9.8  703.25    19.6  696.86    29.4  690.77    49.1  678.21
    58.9  672.61    68.7  669.77    78.5  669.18    85.7  669.14    98.2  669.11
   100.7  669.17     108  669.34   147.2   671.2     157  671.77   166.9  673.29
   176.7  676.11   186.5  679.13   215.9  688.53   235.6  694.68   245.4  697.38
   255.2  699.12     265  700.12   284.6  701.52   294.5   702.7   304.3  705.01
   314.1  707.96   323.9  711.29   343.6  718.48   412.3   745.5   422.1     750
#Mann= 3 , 0 , 0
       0      .1       0    85.7    .045       0   100.7      .1       0
Bank Sta=85.7,100.7
XS Rating Curve= 0 ,0
Exp/Cntr=0.3,0.1

Type RM Length L Ch R = 1 ,31326.2 ,473.1,481.6,490.2
XS GIS Cut Line= 2
     1520694.073      318142.525     1521169.078      318180.267
#Sta/Elev= 30
       0     710     9.7  706.06    29.2  698.85    48.6  691.28    58.4  687.86
    68.1  685.24    77.8  683.31     107  679.03   126.4  676.83   194.5  673.87
   204.2  672.74   223.7  668.56   233.4  667.51   236.4  667.48   243.1  667.41
   251.4  667.44   262.6  667.67   272.3   669.2     282  672.92   301.5   681.2
   311.2  687.17   340.4  709.24   379.3  739.25     389  747.12   418.2  772.52
   427.9  780.15   437.6  786.91   447.3  793.12   466.8  804.69   476.5  810.01
#Mann= 3 , 0 , 0
       0      .1       0   236.4    .045       0   251.4      .1       0
Bank Sta=236.4,251.4
XS Rating Curve= 0 ,0
Exp/Cntr=0.3,0.1

Type RM Length L Ch R = 1 ,30844.6 ,260.7,250.6,240.4
XS GIS Cut Line= 2
     1520540.786      318496.647     1520826.219      318636.478
#Sta/Elev= 30
       0     710     9.6  706.16    19.3  701.85    38.5  692.63    48.2  688.46
    57.8  685.03    67.4  682.39      77  680.29    86.7   678.3    96.3  676.44
   115.6  672.51   125.2   670.8   134.8  669.23   144.5  667.98   154.1  667.25
   170.8  666.74   185.8  666.39   192.6  666.35   202.3  666.88   211.9  668.21
   231.2  671.35   240.8  673.13   250.4  677.46     260  683.52   269.7  690.13
   279.3  696.86     289  703.54   298.6  709.82   308.2  715.34   317.8     720
#Mann= 3 , 0 , 0
       0      .1       0   170.8    .045       0   185.8      .1       0
Bank Sta=170.8,185.8
XS Rating Curve= 0 ,0
Exp/Cntr=0.3,0.1

Type RM Length L Ch R = 1 ,30594   ,277.9,260,242
XS GIS Cut Line= 2
       1520466.9       318752.76     1520760.002      318759.922
#Sta/Elev= 22
       0     710     9.8  704.41    19.6  697.68    39.1  682.89    48.9  676.01
    58.6  670.28    68.4  666.64    71.6  666.24    78.2   665.4    86.6  665.31
      88   665.3   117.3  665.34     127  665.56   136.8  666.11   175.9  669.13
   234.6   674.1   244.3  674.82   254.1  675.65   263.9   677.6   273.6  681.36
   283.4  685.91   293.2  689.99
#Mann= 3 , 0 , 0
       0      .1       0    71.6    .045       0    86.6      .1       0
Bank Sta=71.6,86.6
XS Rating Curve= 0 ,0
Exp/Cntr=0.3,0.1

Type RM Length L Ch R = 1 ,30334   ,535.8,562,588.1
XS GIS Cut Line= 2
     1520600.692      319037.342     1520855.746      318794.819
#Sta/Elev= 26
       0  699.96     9.8  694.51    19.6  690.38    39.1  682.77    48.9  679.05
    58.7  675.48    68.4  672.16    78.2  668.94      88  666.52    97.8  665.54
     104  665.44   127.1  665.15   136.9  665.43   146.6  667.07   156.4  669.92
   166.2  672.46     176  673.95   185.8  674.81   224.9  677.98   244.4  679.39
   254.2  680.26     264  682.29   273.7  685.04   303.1  693.72   312.8  696.77
     352     710
#Mann= 3 , 0 , 0
       0      .1       0     104    .045       0   127.1      .1       0
Bank Sta=104,127.1
XS Rating Curve= 0 ,0
Exp/Cntr=0.3,0.1

Type RM Length L Ch R = 1 ,29772.1 ,700.1,724.4,748.7
XS GIS Cut Line= 2
     1520717.951      319202.429     1521387.241      319462.919
#Sta/Elev= 30
       0     710    29.5  696.05    49.2  687.41      59  683.72    78.7  677.97
    98.4  673.82   108.2  672.32   127.9   670.1   147.6  668.48   206.6  666.17
   265.6  664.67     305   664.9     364   663.8   403.4  664.61   413.2   665.3
     423  666.81   452.6  672.97   462.4  675.54   472.2  679.64   482.1   684.9
   541.1  718.48   600.1  753.73     610  758.14   619.8   761.2   629.6  765.53
   639.5  771.86   678.8  800.31   688.7  806.47   698.5  811.45   718.2     820
#Mann= 3 , 0 , 0
       0      .1       0     364    .045       0   403.4      .1       0
Bank Sta=364,403.4
XS Rating Curve= 0 ,0
Exp/Cntr=0.3,0.1