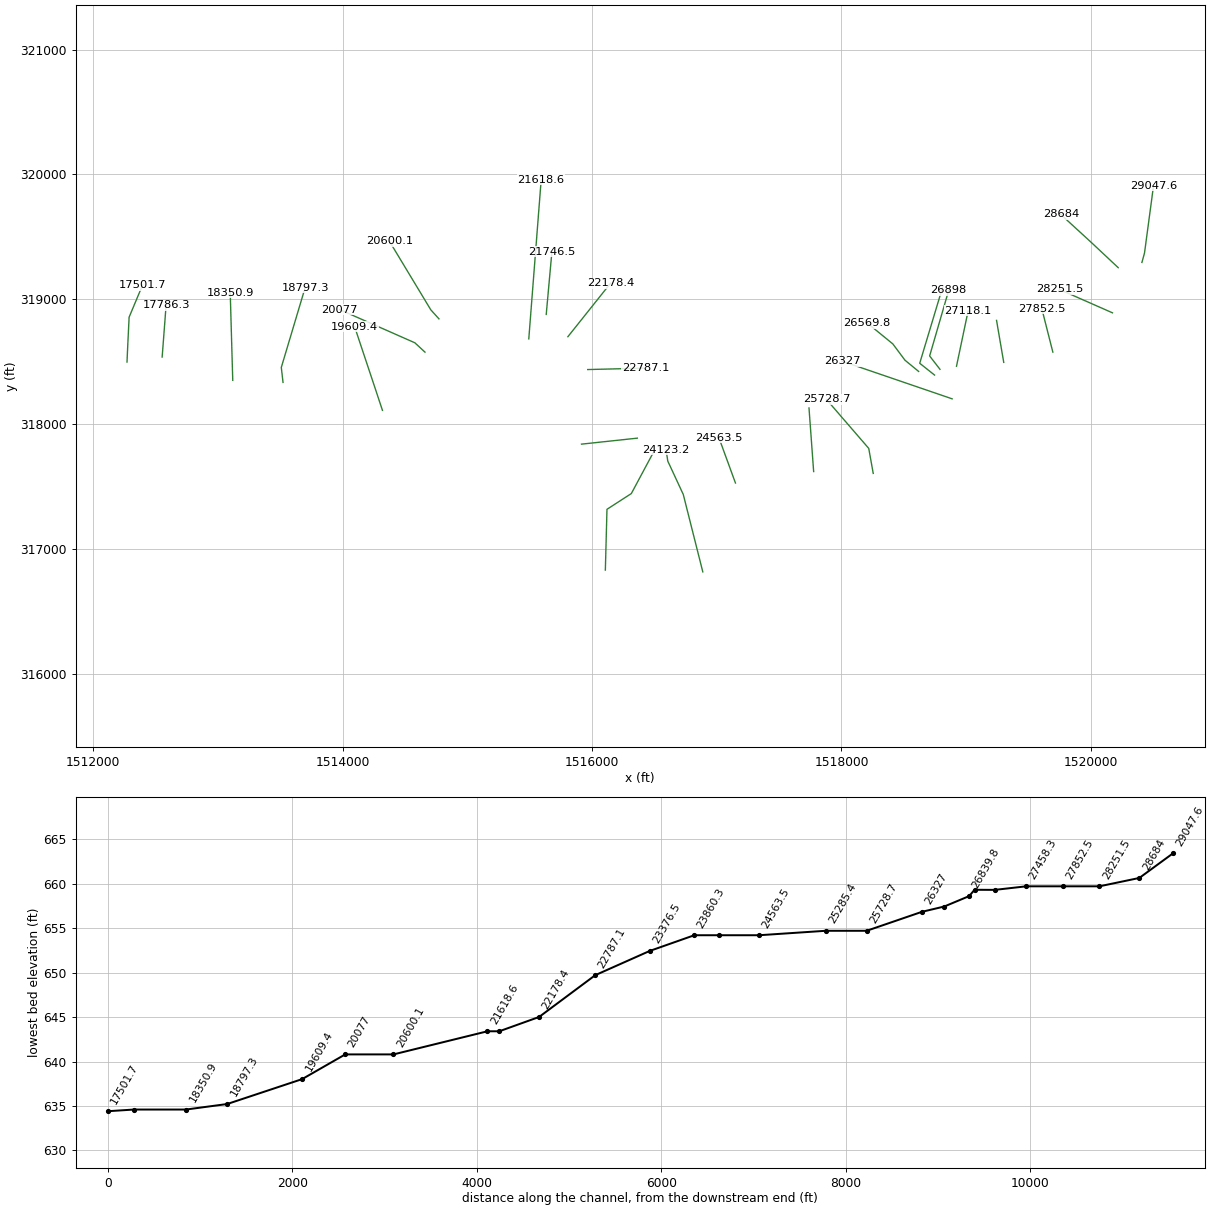
HEC-RAS study McKimCr.prj: McKimCr

--- McKimCr.g01 (geometry) --- (continued)

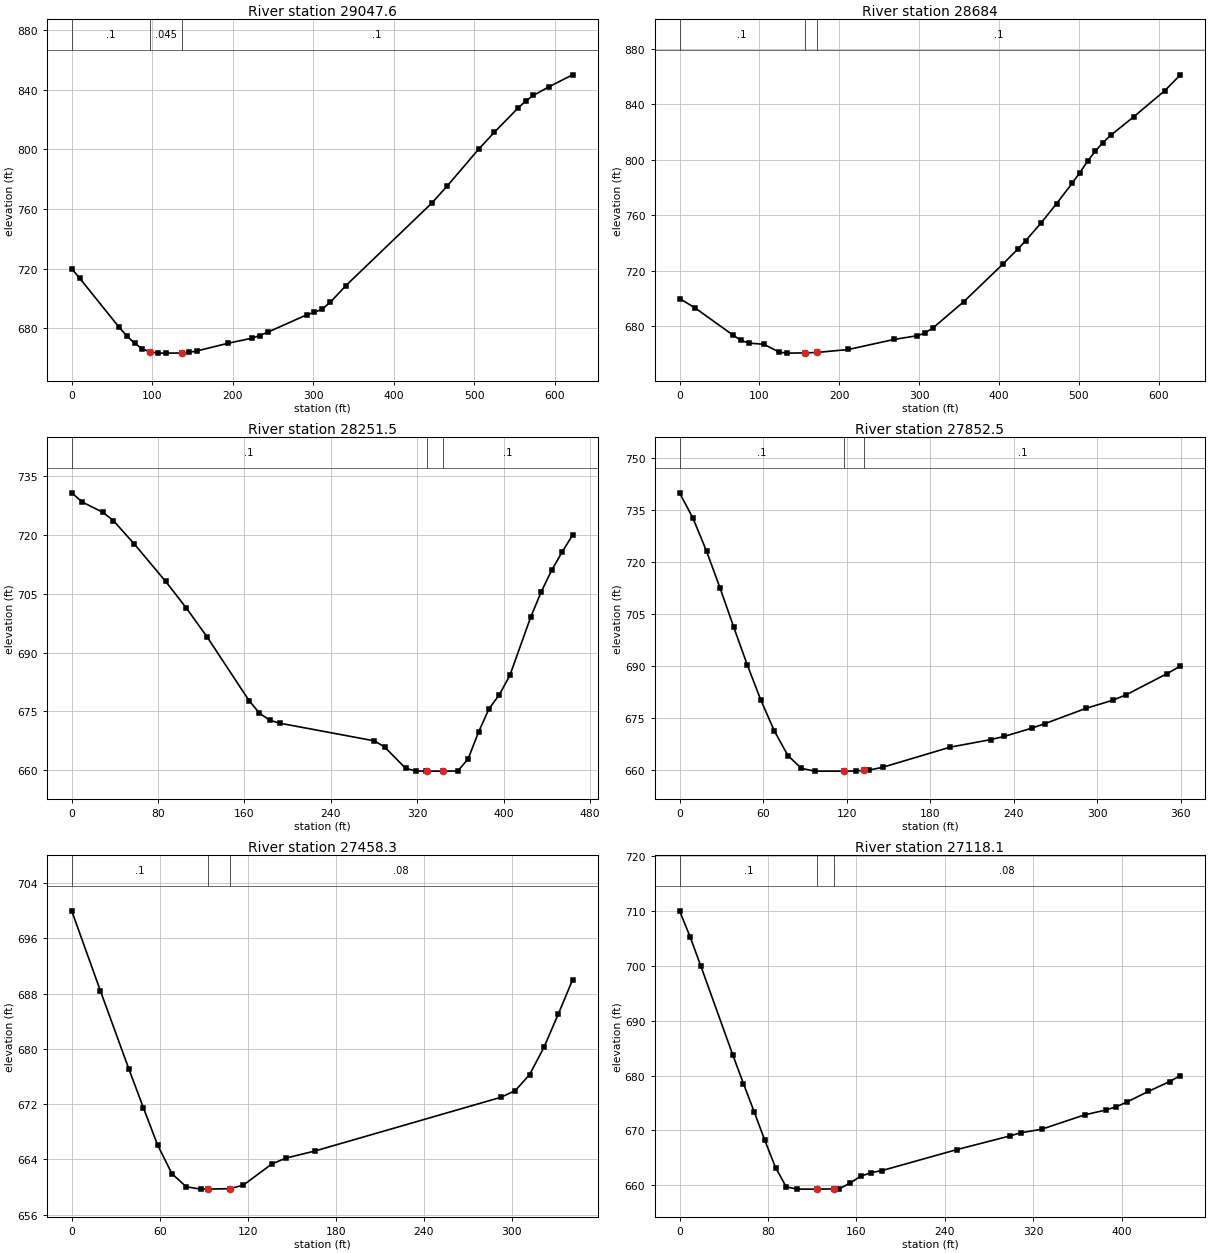
Type RM Length L Ch R = 1 ,29047.6 ,341.4,363.7,386
XS GIS Cut Line= 3
     1520408.314      319294.097     1520429.126      319369.444
     1520501.416      319908.718
#Sta/Elev= 30
       0     720     9.8  713.71    58.6  680.95    68.4  674.95    78.2  669.98
    87.9  666.23    97.6  664.07   107.3  663.44     117   663.4   136.5  663.47
   146.2  663.92   155.9   664.9   194.8  670.07   223.9   673.4   233.6  675.18
   243.3  677.36   291.9  689.06   301.6  690.74   311.4  693.02   321.1  697.38
   340.5  708.57   447.4  763.98   466.8  775.59   505.7  800.18   525.1  811.44
   554.2  827.53     564  832.37   573.7  836.17   593.1  842.03   622.3     850
#Mann= 3 , 0 , 0
       0      .1       0    97.6    .045       0   136.5      .1       0
Bank Sta=97.6,136.5
XS Rating Curve= 0 ,0
Exp/Cntr=0.3,0.1

Type RM Length L Ch R = 1 ,28684   ,423.5,432.5,441.1
XS GIS Cut Line= 3
     1520218.386      319252.324     1519993.794      319462.603
     1519758.067      319678.426
#Sta/Elev= 30
       0  699.99    19.2   693.3    67.3  673.47    76.9  669.87    86.5  667.89
   105.8  666.99     125   661.3   134.6  660.64   156.9   660.8   171.9  661.11
   211.5  663.26   269.2  670.57     298  673.19   307.7  675.24   317.4  678.78
   356.1  697.77   404.5  724.54   423.9  735.73   433.6   741.7   452.9  754.49
   472.3   768.4   491.7  783.04   501.4  790.72     511  798.88   520.7   806.2
   530.4  812.38   540.1  817.63   569.2  831.09   607.9  849.84   627.3  861.18
#Mann= 3 , 0 , 0
       0      .1       0   156.9    .045       0   171.9      .1       0
Bank Sta=156.9,171.9
XS Rating Curve= 0 ,0
Exp/Cntr=0.3,0.1

Type RM Length L Ch R = 1 ,28251.5 ,419.9,399,378
XS GIS Cut Line= 2
      1520172.13      318890.666     1519747.705      319077.562
#Sta/Elev= 30
       0  730.81     9.7  728.46      29  725.81    38.6  723.71      58  717.72
      87  708.18   106.3  701.32   125.6   693.9   164.2  677.74   173.9  674.49
   183.6  672.68   193.2  671.92   280.2  667.44   289.8  665.87   309.2  660.42
   318.8  659.72   328.5   659.7   328.8   659.7   343.8   659.7   357.5  659.72
   367.1  662.81   376.8   669.7   386.5  675.65   396.1  679.24   405.8  684.18
   425.1  699.07   434.8   705.5   444.4  710.98   454.1  715.66   463.8     720
#Mann= 3 , 0 , 0
       0      .1       0   328.8    .045       0   343.8      .1       0
Bank Sta=328.8,343.8
XS Rating Curve= 0 ,0
Exp/Cntr=0.3,0.1

Type RM Length L Ch R = 1 ,27852.5 ,396,394.2,392.5
XS GIS Cut Line= 2
     1519694.331       318575.79     1519605.749      318924.429
#Sta/Elev= 26
       0     740     9.7  732.62    19.4  723.14    29.2  712.41    38.9  701.26
    48.6  690.38    58.3  680.28      68  671.36    77.8   664.2    87.5  660.49
    97.2   659.7   117.8   659.7   126.4  659.73   132.8  659.91   136.1     660
   145.8   660.8   194.4  666.62   223.6   668.8   233.3  669.73   252.8  672.07
   262.5  673.41   291.7  677.79   311.1  680.15   320.8  681.73     350   687.8
   359.7     690
#Mann= 3 , 0 , 0
       0      .1       0   117.8    .045       0   132.8      .1       0
Bank Sta=117.8,132.8
XS Rating Curve= 0 ,0
Exp/Cntr=0.3,0.1

Type RM Length L Ch R = 1 ,27458.3 ,348.7,340.2,331.7
XS GIS Cut Line= 2
     1519300.631      318493.582     1519242.996       318830.08
#Sta/Elev= 20
       0     700    19.5  688.45      39  677.08    48.8  671.52    58.5  666.12
    68.3  661.94      78  660.05    87.8   659.7    92.8   659.7   107.8  659.77
     117  660.28   136.6  663.37   146.3  664.21   165.8  665.22   292.6     673
   302.4  673.97   312.1  676.27   321.9  680.22   331.6     685   341.4  689.99
#Mann= 3 , 0 , 0
       0      .1       0    92.8    .045       0   107.8     .08       0
Bank Sta=92.8,107.8
XS Rating Curve= 0 ,0
Exp/Cntr=0.3,0.1

Type RM Length L Ch R = 1 ,27118.1 ,221.8,220.1,218.4
XS GIS Cut Line= 2
     1518921.967      318462.679     1519015.199      318905.984
#Sta/Elev= 28
       0     710     9.6  705.23    19.3  699.91    48.2  683.72    57.8  678.51
    67.5  673.38    77.1  668.19    86.8  663.24    96.4  659.74     106   659.3
   124.6   659.3   139.6  659.34   144.6  659.38   154.2  660.39   163.8  661.65
   173.5  662.31   183.1  662.68   250.6  666.49   298.8  668.99   308.4  669.55
   327.7  670.22   366.3  672.82   385.5  673.71   395.2  674.32   404.8  675.18
   424.1  677.11   443.4   678.9     453     680
#Mann= 3 , 0 , 0
       0      .1       0   124.6    .045       0   139.6     .08       0
Bank Sta=124.6,139.6
XS Rating Curve= 0 ,0
Exp/Cntr=0.3,0.1

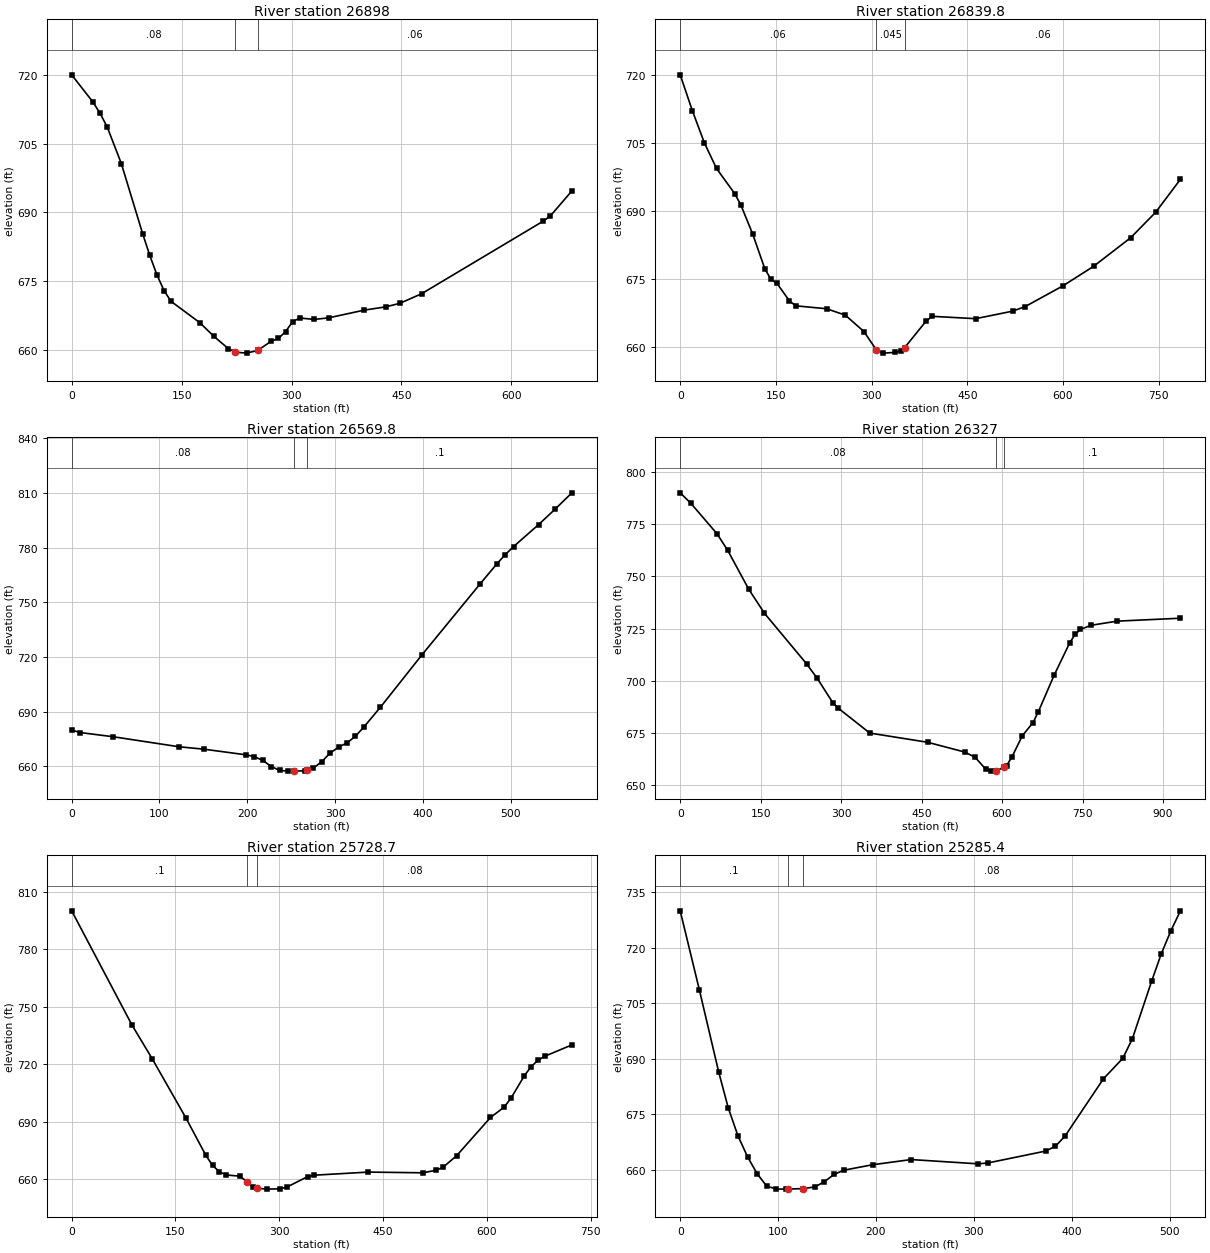
Type RM Length L Ch R = 1 ,26898   ,58.5,58.2,58
XS GIS Cut Line= 3
      1518789.66        318437.8     1518706.626       318545.05
     1518859.369      319070.237
#Sta/Elev= 30
       0     720    29.1  714.05    38.8  711.59    48.4  708.66    67.8  700.63
    96.9  685.33   106.6  680.62   116.3  676.39     126  672.96   135.6   670.6
   174.7  665.97   194.2  662.95   213.8  660.29   223.5  659.52   238.8  659.31
   253.8   659.9   272.4  661.91   282.1   662.5   291.9  664.01   301.7   666.2
   311.4  666.97     331  666.66   350.5     667   399.3  668.69   428.6   669.4
   448.2  670.19   477.5  672.26   643.5  688.09   653.3  689.24   682.6  694.68
#Mann= 3 , 0 , 0
       0     .08       0   223.5    .045       0   253.8     .06       0
Bank Sta=223.5,253.8
XS Rating Curve= 0 ,0
Exp/Cntr=0.3,0.1

Type RM Length L Ch R = 1 ,26839.8 ,248.7,269.9,291.2
XS GIS Cut Line= 3
     1518745.994      318392.044     1518627.164      318486.469
     1518809.456      319091.938
#Sta/Elev= 30
       0     720      19   712.1    37.9  704.99    56.9  699.34    85.4   693.8
    94.9  691.34   113.8  684.81   132.8  677.14   142.3  674.89   151.8  673.97
   171.2  670.13     181  669.04   229.6  668.39   258.8  666.98     288  663.36
   307.4  659.33   317.2   658.6     337  658.75   346.3   659.1     352  659.84
   385.2  665.62     395  666.72   463.1   666.2   521.4  667.87   540.9  668.88
   599.3  673.39   647.9  677.74   706.3  684.08   745.2  689.66   784.1  696.94
#Mann= 3 , 0 , 0
       0     .06       0   307.4    .045       0     352     .06       0
Bank Sta=307.4,352
XS Rating Curve= 0 ,0
Exp/Cntr=0.3,0.1

Type RM Length L Ch R = 1 ,26569.8 ,229.3,242.9,256.5
XS GIS Cut Line= 4
     1518618.321      318421.293     1518509.198      318510.731
      1518411.65      318641.419     1518205.772      318809.473
#Sta/Elev= 30
       0  679.98     9.4   678.6      47   676.3   122.3  670.79   150.7  669.46
   198.6  666.37   208.2  665.36   217.8  663.29   227.4  659.95     237  657.82
   246.6  657.43     253  657.44   265.8  657.62     268  657.96   275.4  659.12
     285  662.65   294.6  667.42   304.2  670.58   313.7  672.95   323.2  676.52
   332.6  681.44   351.6  692.36   399.1  721.18   465.5  760.16   484.5  771.09
     494  776.14   503.5  780.54     532  792.59     551  801.14   569.9     810
#Mann= 3 , 0 , 0
       0     .08       0     253    .045       0     268      .1       0
Bank Sta=253,268
XS Rating Curve= 0 ,0
Exp/Cntr=0.3,0.1

Type RM Length L Ch R = 1 ,26327   ,610.2,598.3,586.4
XS GIS Cut Line= 2
     1518887.269      318201.557     1518004.884      318503.234
#Sta/Elev= 30
       0     790    19.6  785.06    68.7  770.39    88.3  762.58   127.6  743.94
   157.1  732.35   235.6  708.17   255.2  701.32   284.7   689.5   294.5  686.98
   353.4  675.04   461.4  670.63   530.1  665.98   549.7  663.48   569.3  657.84
   579.2  656.83   589.3  657.08   604.3  658.69   608.6  659.49   618.4   663.6
     638  673.86   657.7  680.02   667.5  685.17   696.9  702.62   726.4  718.36
   736.2  722.23     746  724.61   765.7  726.61   814.7   728.6   932.5     730
#Mann= 3 , 0 , 0
       0     .08       0   589.3    .045       0   604.3      .1       0
Bank Sta=589.3,604.3
XS Rating Curve= 0 ,0
Exp/Cntr=0.3,0.1

Type RM Length L Ch R = 1 ,25728.7 ,458.6,443.2,427.8
XS GIS Cut Line= 3
     1518254.404      317604.109     1518218.501       317804.55
     1517879.053      318197.322
#Sta/Elev= 30
       0  800.01    87.3  740.28   116.4  722.75   164.8  692.04   193.9  672.32
   203.6  667.06   213.4   663.8   223.2   662.1   242.8  661.48   253.4   658.6
   262.4  655.74   268.4  655.15     282   654.7   301.6  654.86   311.4  655.84
   340.8  661.21   350.6  661.98   428.9   663.6   507.3  663.22   526.9  664.57
   536.7  666.13   556.2  672.13   605.2  692.11   624.8  697.48   634.6  702.07
   654.2  713.93     664  718.71   673.8  721.97   683.6  724.08   722.8     730
#Mann= 3 , 0 , 0
       0      .1       0   253.4    .045       0   268.4     .08       0
Bank Sta=253.4,268.4
XS Rating Curve= 0 ,0
Exp/Cntr=0.3,0.1

Type RM Length L Ch R = 1 ,25285.4 ,715.7,722,728.3
XS GIS Cut Line= 2
     1517776.806       317619.11     1517739.581      318128.775
#Sta/Elev= 30
       0  729.98    19.6  708.58    39.3  686.41    49.1  676.66      59  669.11
    68.8  663.45    78.6  658.86    88.4   655.5    98.3  654.73   108.1   654.7
   110.3  654.72   125.3  654.84   137.6  655.29   147.4  656.73   157.2  658.68
   167.1  659.82   196.6   661.3   235.9   662.7   304.6  661.54   314.5  661.79
   373.4     665   383.3   666.3   393.1  669.04   432.4  684.56   452.1  690.08
   461.9  695.37   481.5  710.88   491.4  718.33   501.2  724.57     511     730
#Mann= 3 , 0 , 0
       0      .1       0   110.3    .045       0   125.3     .08       0
Bank Sta=110.3,125.3
XS Rating Curve= 0 ,0
Exp/Cntr=0.3,0.1

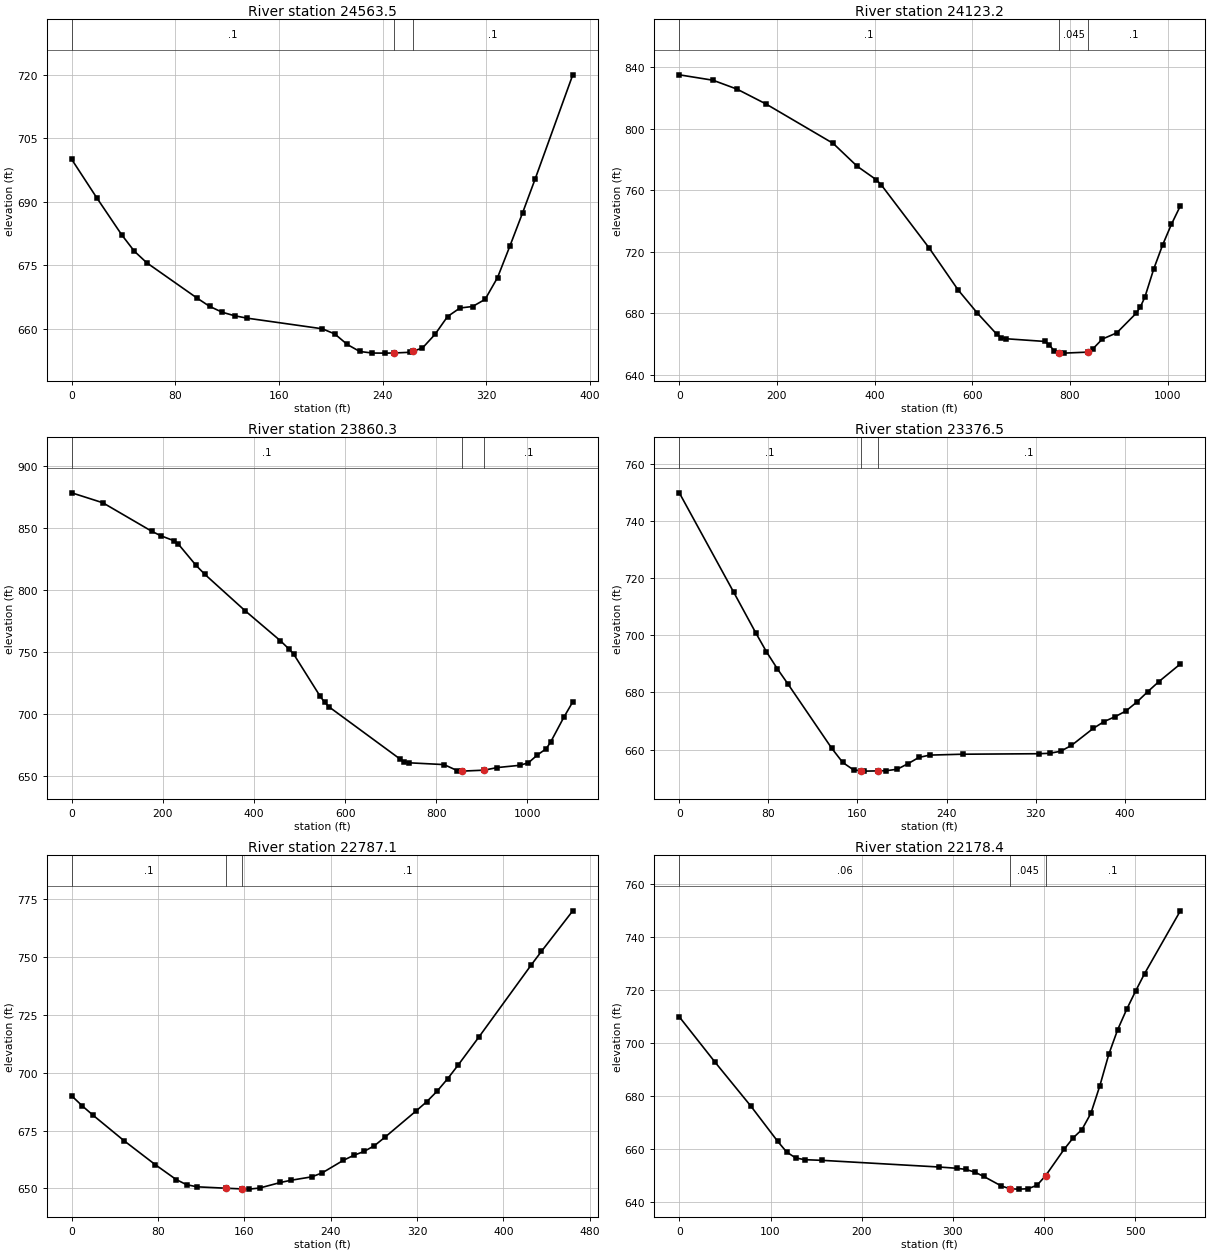
Type RM Length L Ch R = 1 ,24563.5 ,438.4,440.3,442.2
XS GIS Cut Line= 2
     1517149.944      317527.267     1517017.171      317890.641
#Sta/Elev= 30
       0     700    19.3  690.94    38.7  682.13    48.4  678.28      58  675.55
    96.7  667.23   106.4  665.27   116.1  663.88   125.7  663.04   135.4  662.47
   193.4  659.96   203.1  658.74   212.8  656.24   222.4  654.59   232.1  654.22
   241.8   654.2   248.9  654.23   261.1   654.4   263.9  654.69   270.8   655.4
   280.5  658.63   290.2  662.85   299.8  664.87   309.5  665.22   319.2  666.91
   328.8  672.06   338.5  679.64   348.2  687.41   357.9  695.42   386.9     720
#Mann= 3 , 0 , 0
       0      .1       0   248.9    .045       0   263.9      .1       0
Bank Sta=248.9,263.9
XS Rating Curve= 0 ,0
Exp/Cntr=0.3,0.1

Type RM Length L Ch R = 1 ,24123.2 ,283.9,262.9,241.8
XS GIS Cut Line= 4
     1516888.276      316815.145     1516731.739      317435.436
     1516607.348      317703.175     1516593.944      317793.113
#Sta/Elev= 30
       0  835.23    68.9  831.72   118.1  825.94   177.2  816.32     315  790.63
   364.2  775.75   403.5  766.95   413.4  763.69   511.8  722.48   570.8  695.33
   610.2  680.27   649.6  666.61   659.4  664.24   669.3  663.55     748  661.81
   757.8  659.53   767.7  655.54   777.5  654.27   787.4   654.2   836.6  654.86
   846.4  656.86   866.1  663.34   895.6  667.36     935  679.99     944  684.27
   953.2  690.58   971.3  708.87   989.5  724.52  1007.7  738.08  1025.9     750
#Mann= 3 , 0 , 0
       0      .1       0   777.5    .045       0   836.6      .1       0
Bank Sta=777.5,836.6
XS Rating Curve= 0 ,0
Exp/Cntr=0.3,0.1

Type RM Length L Ch R = 1 ,23860.3 ,506.5,483.8,461
XS GIS Cut Line= 4
     1516107.026      316829.468     1516120.004      317316.514
     1516315.373      317442.762     1516494.747      317777.581
#Sta/Elev= 30
       0  878.41    68.2  870.42   175.4  847.49   194.9  843.93   224.1  839.85
   233.9  837.14   272.8  819.99   292.3  812.69     380  783.59     458  759.24
   477.5  752.33   487.2  748.42   545.4  714.41   555.1  709.64   564.8  705.94
   719.8  664.17   729.6  661.94   739.3  660.93   817.2  659.46   846.4  654.57
   856.2   654.2   904.9  654.97   934.1  657.08   982.8  658.87  1002.3  660.89
  1021.8  667.17  1041.2  672.18    1051  677.56  1080.2  697.68  1099.7     710
#Mann= 3 , 0 , 0
       0      .1       0   856.2    .045       0   904.9      .1       0
Bank Sta=856.2,904.9
XS Rating Curve= 0 ,0
Exp/Cntr=0.3,0.1

Type RM Length L Ch R = 1 ,23376.5 ,591.1,589.4,587.6
XS GIS Cut Line= 2
     1515916.023      317838.619      1516363.51       317886.62
#Sta/Elev= 30
       0     750    48.9  715.12    68.5  701.03    78.3  694.26      88  688.34
    97.8  682.85     137  660.39   146.8  655.46   156.5  652.86     163  652.57
   166.3  652.43     178  652.51   185.9  652.58   195.7  653.09   205.5  655.06
   215.2  657.24     225  658.05   254.4  658.36   322.9  658.53   332.6  658.68
   342.4  659.39   352.2  661.44   371.8  667.42   381.6  669.82   391.4  671.52
   401.1  673.51   410.9  676.64   420.7  680.28   430.5  683.75     450     690
#Mann= 3 , 0 , 0
       0      .1       0     163    .045       0     178      .1       0
Bank Sta=163,178
XS Rating Curve= 0 ,0
Exp/Cntr=0.3,0.1

Type RM Length L Ch R = 1 ,22787.1 ,589,608.7,628.4
XS GIS Cut Line= 2
     1515965.715      318436.108     1516430.007      318447.642
#Sta/Elev= 30
       0  690.01     9.7  685.72    19.4   681.8    48.4  670.67    77.4   660.3
    96.8  653.86   106.4  651.64   116.1  650.71   143.2   650.1   158.2  649.79
   164.5  649.71   174.2  650.19   193.5  652.59   203.2  653.54   222.5  655.02
   232.2  656.75   251.6  662.12   261.2  664.27   270.9  665.99   280.6   668.5
   290.3  672.14   319.3  683.55     329  687.48   338.6  692.02   348.3  697.36
     358  703.24   377.4  715.46   425.7  746.48   435.4  752.51   464.4     770
#Mann= 3 , 0 , 0
       0      .1       0   143.2    .045       0   158.2      .1       0
Bank Sta=143.2,158.2
XS Rating Curve= 0 ,0
Exp/Cntr=0.3,0.1

Type RM Length L Ch R = 1 ,22178.4 ,418.7,432,445.2
XS GIS Cut Line= 2
     1515806.544      318699.131     1516149.326       319128.48
#Sta/Elev= 30
       0     710    39.2   692.9    78.5  676.31   107.9  663.03   117.7  659.01
   127.5  656.79   137.4  656.12     157  655.86   284.5  653.36   304.1  652.88
   313.9  652.47   323.8  651.44   333.6  649.84   353.2  646.18     363  645.11
   372.8  645.01   382.6  645.16   392.4  646.52   401.8  650.15   421.9  660.01
   431.7  664.29   441.5   667.5   451.3  673.62   461.1  683.99   470.9  695.84
   480.7   705.2   490.5  712.81   500.4  719.79   510.2  726.34   549.4     750
#Mann= 3 , 0 , 0
       0     .06       0     363    .045       0   401.8      .1       0
Bank Sta=363,401.8
XS Rating Curve= 0 ,0
Exp/Cntr=0.3,0.1

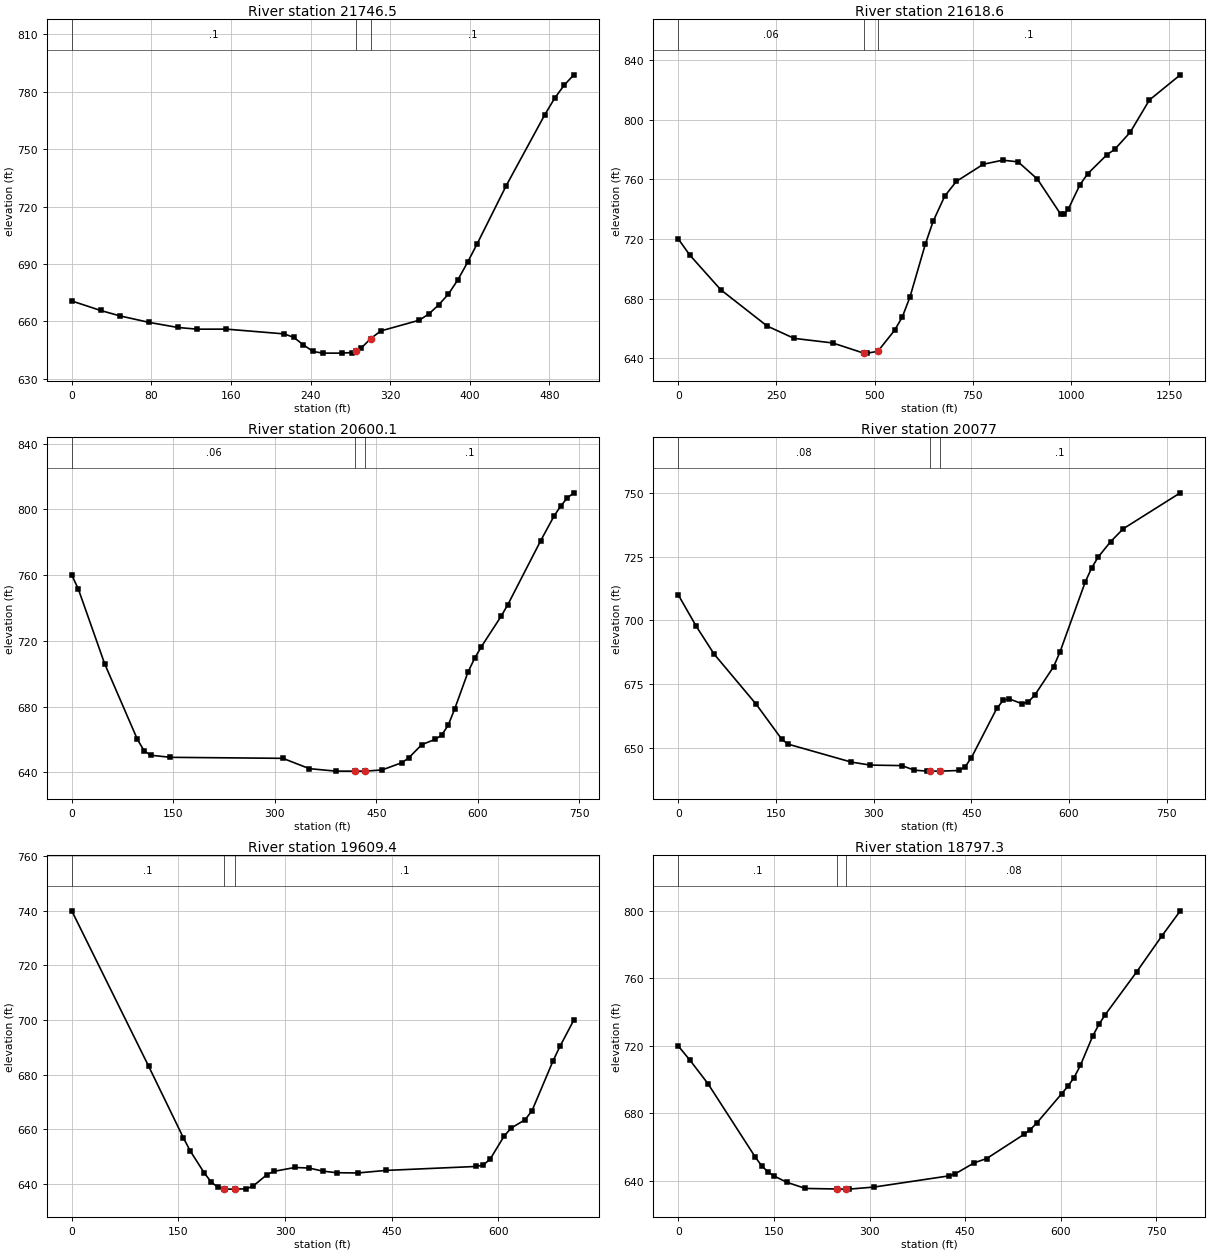
Type RM Length L Ch R = 1 ,21746.5 ,127.6,127.9,128.2
XS GIS Cut Line= 2
     1515633.067      318877.645      1515678.64      319380.249
#Sta/Elev= 30
       0  670.65    29.1  665.67    48.5  662.84    77.6  659.47   106.8  656.79
   126.2  655.91   155.3  655.94   213.5  653.45   223.2  651.62   232.9  647.69
   242.6  644.26   252.3   643.4   271.7   643.4   281.4  643.72   285.6  644.77
   291.2  646.17   300.6  651.03   310.6  654.98   349.4  660.61   359.1  663.94
   368.8   668.6   378.5  674.17   388.2  681.77   397.9  690.88   407.6  700.59
   436.7  730.87   475.6  768.04   485.3  776.48     495  783.42   504.7  788.79
#Mann= 3 , 0 , 0
       0      .1       0   285.6    .045       0   300.6      .1       0
Bank Sta=285.6,300.6
XS Rating Curve= 0 ,0
Exp/Cntr=0.3,0.1

Type RM Length L Ch R = 1 ,21618.6 ,1004.4,1018.5,1032.7
XS GIS Cut Line= 2
     1515493.309      318682.137     1515592.592      319956.128
#Sta/Elev= 30
       0     720    29.5  709.11   108.1  685.92   226.1  661.59   294.9   653.3
   393.2  650.21   471.8  643.41   481.6   643.4     508   644.6   550.5  658.68
   570.1  667.52   589.8  681.06   629.1  716.66   648.8  731.81   678.2  748.64
   707.7  758.52   776.5  770.05   825.7  772.76     865  771.64   914.2  760.06
   973.1  736.62     983  736.69   992.8  740.01  1022.3  756.25  1041.9  763.62
  1091.1  776.42  1110.8  780.01  1150.1  791.42  1199.2  813.13  1277.8  829.99
#Mann= 3 , 0 , 0
       0     .06       0   471.8    .045       0     508      .1       0
Bank Sta=471.8,508
XS Rating Curve= 0 ,0
Exp/Cntr=0.3,0.1

Type RM Length L Ch R = 1 ,20600.1 ,509.4,523.1,536.9
XS GIS Cut Line= 3
     1514773.081      318842.353     1514708.003      318914.233
     1514374.699      319466.102
#Sta/Elev= 30
       0     760     9.7   751.5    48.5  706.16      97  660.05   106.7  653.28
   116.5  650.48   145.8  649.19   311.9  648.58   350.9  642.31     390   640.8
   418.6   640.8   433.6   640.8   458.4  641.51   487.7  645.96   497.5  648.74
     517  656.89   536.5  660.06   546.3   662.6   556.1  668.75   565.8  678.74
   585.4  701.09   595.2  709.46   604.9  716.34   634.2   734.9     644  741.89
   692.8  780.96   712.4  795.87   722.1  801.84   731.9  806.89   741.7  810.01
#Mann= 3 , 0 , 0
       0     .06       0   418.6    .045       0   433.6      .1       0
Bank Sta=418.6,433.6
XS Rating Curve= 0 ,0
Exp/Cntr=0.3,0.1

Type RM Length L Ch R = 1 ,20077   ,486.6,467.5,448.5
XS GIS Cut Line= 3
     1514661.079      318575.595     1514580.278      318650.288
     1513975.839      318917.112
#Sta/Elev= 30
       0     710    27.5   697.7      55  686.75   119.8     667   158.6  653.43
   168.3  651.41   265.5  644.36   294.6  643.17   343.2  642.97   362.7  641.16
   382.1   640.8   386.8   640.8   401.8   640.8   430.7  641.05   440.4  642.49
   450.1  646.08     489  665.39   498.7  668.52   508.4  669.12   527.8  667.24
   537.6     668   547.3   670.6   576.4  681.84   586.1  687.58     625  715.13
   634.7  720.51   644.4  724.71   663.9  730.87   683.3  735.92   770.8     750
#Mann= 3 , 0 , 0
       0     .08       0   386.8    .045       0   401.8      .1       0
Bank Sta=386.8,401.8
XS Rating Curve= 0 ,0
Exp/Cntr=0.3,0.1

Type RM Length L Ch R = 1 ,19609.4 ,828.1,812.2,796.2
XS GIS Cut Line= 2
     1514320.326      318109.157     1514097.239      318778.996
#Sta/Elev= 30
       0     740   107.9  683.16   156.9  656.84   166.7  651.97   186.3  643.95
   196.1   640.6   205.9  638.62   214.4   638.1   215.7  638.02   229.4  638.02
   245.1  638.13     255  639.13   274.6  643.36   284.4  644.54   313.8  645.95
   333.4  645.76     353  644.62   372.6  644.03     402  643.94   441.3  644.87
   568.7  646.33   578.5  646.85   588.3     649     608  657.47   617.8  660.38
   637.4  663.45   647.2  666.76   676.6  684.92   686.4   690.3     706  699.98
#Mann= 3 , 0 , 0
       0      .1       0   214.4    .045       0   229.4      .1       0
Bank Sta=214.4,229.4
XS Rating Curve= 0 ,0
Exp/Cntr=0.3,0.1

Type RM Length L Ch R = 1 ,18797.3 ,436.3,446.4,457.1
XS GIS Cut Line= 3
     1513523.084      318332.928     1513509.348      318453.201
     1513700.249      319091.744
#Sta/Elev= 30
       0     720    18.6  711.45    46.6  697.67   121.1  654.04   130.9     649
   140.7  645.43   150.5  642.98   170.1   639.3   199.5  635.62   248.9   635.3
   263.9  635.23   268.1  635.22   307.3  636.45   424.9  643.08   434.7  644.33
   464.1  650.77   483.7  653.31   542.5  667.68   552.3  670.48   562.1  674.28
   601.3  691.63   611.1   696.1   620.9  701.31   630.7  708.43   650.3  726.02
   660.1  732.88   669.9   738.6   718.9  763.77   758.1  784.89   787.5     800
#Mann= 3 , 0 , 0
       0      .1       0   248.9    .045       0   263.9     .08       0
Bank Sta=248.9,263.9
XS Rating Curve= 0 ,0
Exp/Cntr=0.3,0.1

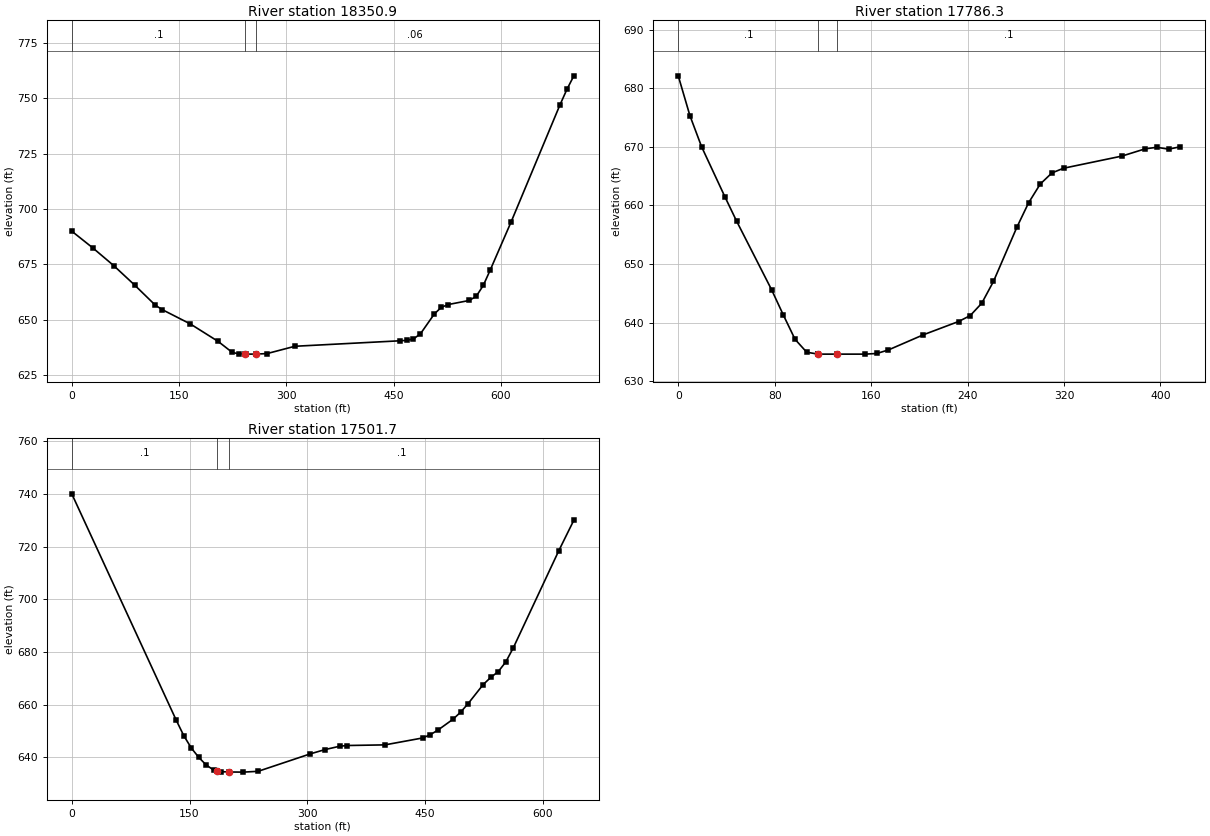
Type RM Length L Ch R = 1 ,18350.9 ,567.2,564.6,561.4
XS GIS Cut Line= 2
     1513120.079      318349.755     1513099.856      319051.587
#Sta/Elev= 30
       0     690    29.3  682.49    58.5  674.53    87.8  665.75     117   656.6
   126.8   654.6   165.8   648.2   204.8   640.3   224.3   635.4     234  634.67
   242.4  634.61   243.8   634.6   257.4  634.61     273  634.84     312  638.14
   458.3   640.6   468.1   640.8   477.8  641.43   487.6  643.76   507.1  652.74
   516.8  655.71   526.6  656.95   555.8  658.78   565.6  660.65   575.4  665.53
   585.1  672.44   614.4   694.2   682.6  746.85   692.4  753.89   702.1     760
#Mann= 3 , 0 , 0
       0      .1       0   242.4    .045       0   257.4     .06       0
Bank Sta=242.4,257.4
XS Rating Curve= 0 ,0
Exp/Cntr=0.3,0.1

Type RM Length L Ch R = 1 ,17786.3 ,284,284.6,285.1
XS GIS Cut Line= 2
     1512554.162      318536.501     1512585.867      318951.789
#Sta/Elev= 30
       0  682.15     9.7  675.34    19.4  670.02    38.7  661.49    48.4  657.33
    77.5  645.58    87.2  641.28    96.9  637.13   106.6  634.92   116.2   634.6
   116.3   634.6   131.3   634.6     155   634.6   164.7  634.71   174.4  635.32
   203.4  637.91   232.5  640.17   242.2  641.18   251.8   643.3   261.5  647.02
   280.9  656.27   290.6  660.44   300.3  663.66     310  665.56   319.6  666.36
   368.1  668.44   387.4  669.68   397.1  669.94   406.8  669.62   416.5  670.03
#Mann= 3 , 0 , 0
       0      .1       0   116.3    .045       0   131.3      .1       0
Bank Sta=116.3,131.3
XS Rating Curve= 0 ,0
Exp/Cntr=0.3,0.1

Type RM Length L Ch R = 1 ,17501.7 ,509.3,499.4,489.5
XS GIS Cut Line= 4
     1512272.286      318496.054     1512279.713       318657.55
     1512289.317      318855.944     1512397.339      319113.233
#Sta/Elev= 30
       0     740   133.1  654.06   142.6  648.26   152.2  643.56   161.7     640
   171.1  637.14   180.6  635.21   185.3  634.89     190  634.57   200.3  634.47
   218.4  634.41   237.3  634.72   303.5  641.32   322.5  642.97   341.4  644.25
   350.8  644.51   398.8  644.75   446.9  647.38   456.5  648.61   466.1  650.33
   485.4  654.47     495  657.12   504.6  660.38   523.9  667.65   533.5  670.35
   543.1  672.56   552.7  676.25   562.4  681.69   620.1   718.4   639.3     730
#Mann= 3 , 0 , 0
       0      .1       0   185.3    .045       0   200.3      .1       0
Bank Sta=185.3,200.3
XS Rating Curve= 0 ,0
Exp/Cntr=0.3,0.1