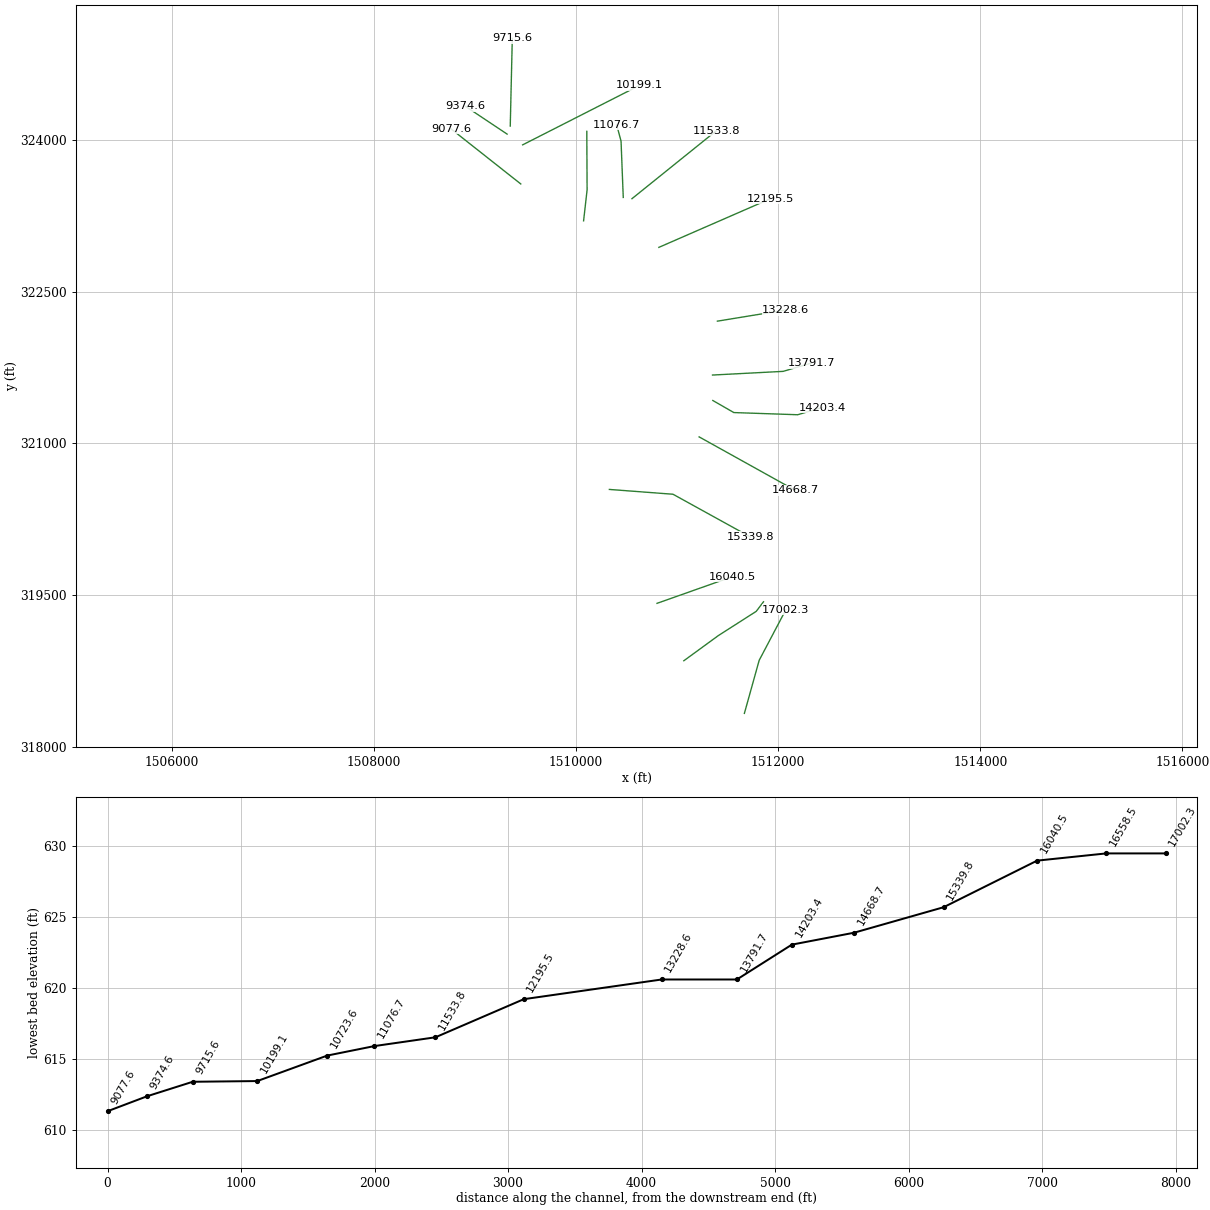
HEC-RAS study McKimCr.prj: McKimCr

--- McKimCr.g01 (geometry) --- (continued)

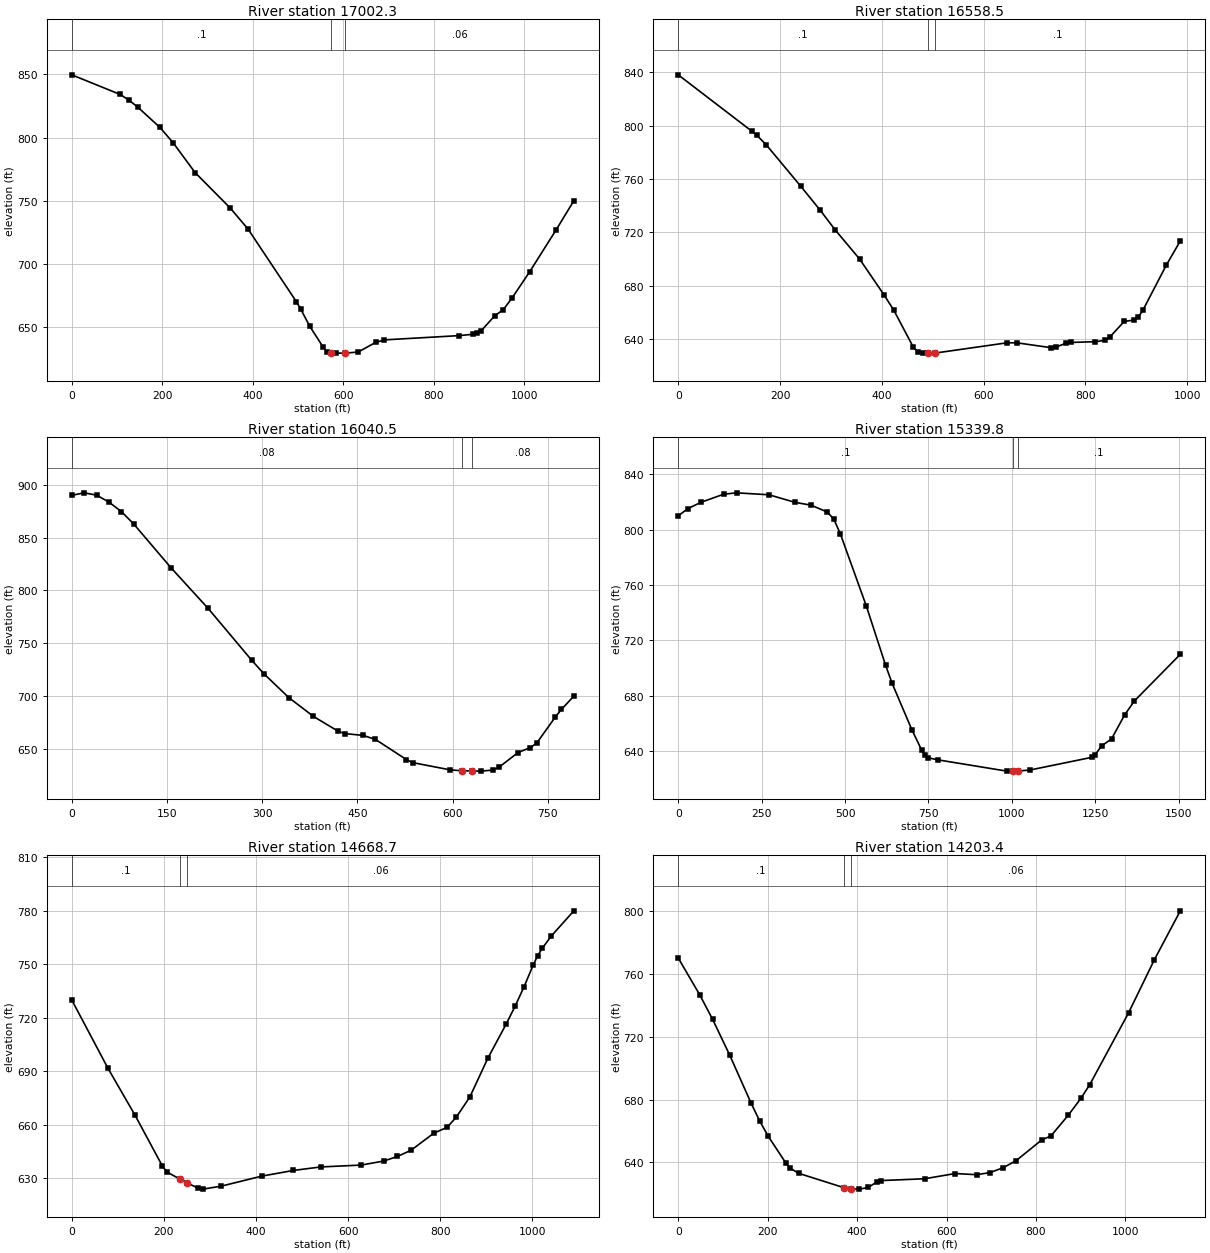
Type RM Length L Ch R = 1 ,17002.3 ,455.6,443.8,432
XS GIS Cut Line= 3
     1511666.054      318328.166     1511812.418      318853.114
     1512075.529      319352.446
#Sta/Elev= 30
       0  849.62     107  834.09   126.5  829.54     146  824.02   194.6   808.1
   223.8  795.97   272.5  772.31   350.3  744.18   389.3  727.72   496.3  670.19
     506  664.28   525.5  650.94   554.7  634.68   564.4  630.32   572.3  629.72
   583.9   629.5   603.4   629.5   632.6  630.34   671.5  637.99   690.9  639.98
   856.4  643.36   885.6  644.38   895.3  645.24     905  647.32   934.2   658.9
   953.7  663.94   973.1  673.22  1012.1  694.02  1070.5  727.14  1109.4  750.01
#Mann= 3 , 0 , 0
       0      .1       0   572.3    .045       0   603.4     .06       0
Bank Sta=572.3,603.4
XS Rating Curve= 0 ,0
Exp/Cntr=0.3,0.1

Type RM Length L Ch R = 1 ,16558.5 ,523.3,518,512.8
XS GIS Cut Line= 4
     1511067.095      318848.999     1511409.359      319098.531
     1511783.073      319337.487      1511855.29      319432.333
#Sta/Elev= 30
       0  838.06   144.4  795.86     154  792.93   173.3  785.42   240.7  754.57
   279.2  736.46     308     722   356.2  700.07   404.3  673.17   423.6   661.6
   462.1  633.78   471.8   630.1   481.4   629.5   490.4   629.5   505.4  629.58
   645.4   637.2   664.6  637.26   732.2  633.61   741.8  633.96   761.1  636.86
   770.7  637.49   818.9  638.07   838.2  639.04   847.9  641.58   876.3  653.26
   894.7  654.23   903.8  656.54     913  661.74   958.8  695.37   986.4  713.58
#Mann= 3 , 0 , 0
       0      .1       0   490.4    .045       0   505.4      .1       0
Bank Sta=490.4,505.4
XS Rating Curve= 0 ,0
Exp/Cntr=0.3,0.1

Type RM Length L Ch R = 1 ,16040.5 ,721.9,700.7,679.2
XS GIS Cut Line= 2
     1510801.722      319417.038     1511547.457       319680.67
#Sta/Elev= 30
       0     890    19.5  892.39    39.1  890.18    58.6  883.61    78.1  874.64
    97.6  862.93   156.2  821.54   214.8  783.02   283.2  734.12   302.7  721.13
   341.8  698.65   380.8  680.74   419.9  666.66   429.7  664.56     459  662.79
   478.5  658.97   527.3   639.9   537.1  637.03   595.7  630.24     615  629.32
     630  629.16   644.5  628.99     664  629.99   673.8  633.02   703.1  646.58
   722.6  651.32   732.4  655.42   761.7  680.09   771.4  687.38     791     700
#Mann= 3 , 0 , 0
       0     .08       0     615    .045       0     630     .08       0
Bank Sta=615,630
XS Rating Curve= 0 ,0
Exp/Cntr=0.3,0.1

Type RM Length L Ch R = 1 ,15339.8 ,669.3,671.2,673
XS GIS Cut Line= 3
     1510330.173      320544.095     1510959.842      320496.459
     1511724.649      320074.398
#Sta/Elev= 30
       0     810    29.1  815.16      68   819.7     136  825.53   174.9  826.55
     272  825.14   349.7   819.7   398.3  817.62   446.9  812.67   466.3  807.57
   485.8  797.02   563.5  745.08   621.8  701.96   641.3  688.96   700.2  655.64
   729.6  640.91   739.4  637.13   749.2  635.32   778.7  633.82   984.8   625.7
  1003.4  625.74  1018.4   625.8  1053.5  626.46    1240  635.67  1249.8  637.57
  1269.4  643.97  1298.9  648.97  1338.2  666.32  1367.6  676.42    1505     710
#Mann= 3 , 0 , 0
       0      .1       0  1003.4    .045       0  1018.4      .1       0
Bank Sta=1003.4,1018.4
XS Rating Curve= 0 ,0
Exp/Cntr=0.3,0.1

Type RM Length L Ch R = 1 ,14668.7 ,454.4,465.3,476.1
XS GIS Cut Line= 2
     1511218.294      321064.102     1512171.097      320534.252
#Sta/Elev= 30
       0     730    78.6  691.67   137.5  665.31   196.4  637.02   206.3  633.58
   235.7  629.37   250.7  627.34     275  624.38   284.8   623.9   324.1  625.54
   412.5  631.19   481.3  634.38   540.2  636.33   628.6   637.4   677.7  639.67
   707.2  642.24   736.6  645.68   785.7  655.19   815.2  658.63   834.8   664.2
   864.3  675.56   903.6   697.4   942.9   716.3   962.5  726.42   982.2  737.47
  1001.8  749.55  1011.6  754.77  1021.5  758.95  1041.1  765.82  1090.2     780
#Mann= 3 , 0 , 0
       0      .1       0   235.7    .045       0   250.7     .06       0
Bank Sta=235.7,250.7
XS Rating Curve= 0 ,0
Exp/Cntr=0.3,0.1

Type RM Length L Ch R = 1 ,14203.4 ,410.2,411.7,413.3
XS GIS Cut Line= 4
     1511353.641       321424.17     1511561.691      321304.702
     1512193.471      321283.157     1512433.831      321354.445
#Sta/Elev= 30
       0     770      48  746.63    76.8  731.04   115.2  708.22   163.1  677.61
   182.3   666.3   201.5  656.56   239.9  639.98   249.6  636.54   269.1  633.13
   370.9  623.95   385.9  623.19   405.2  623.06   424.7  624.12   444.1  627.58
   453.9   628.5   551.1  629.66   619.2  632.97   667.8  632.23     697  633.57
   726.2  636.61   755.4  641.12   813.7  654.52   833.2  656.77   872.1     670
     901  680.97   920.3   689.5  1007.1  735.15  1064.9  768.98  1122.8     800
#Mann= 3 , 0 , 0
       0      .1       0   370.9    .045       0   385.9     .06       0
Bank Sta=370.9,385.9
XS Rating Curve= 0 ,0
Exp/Cntr=0.3,0.1

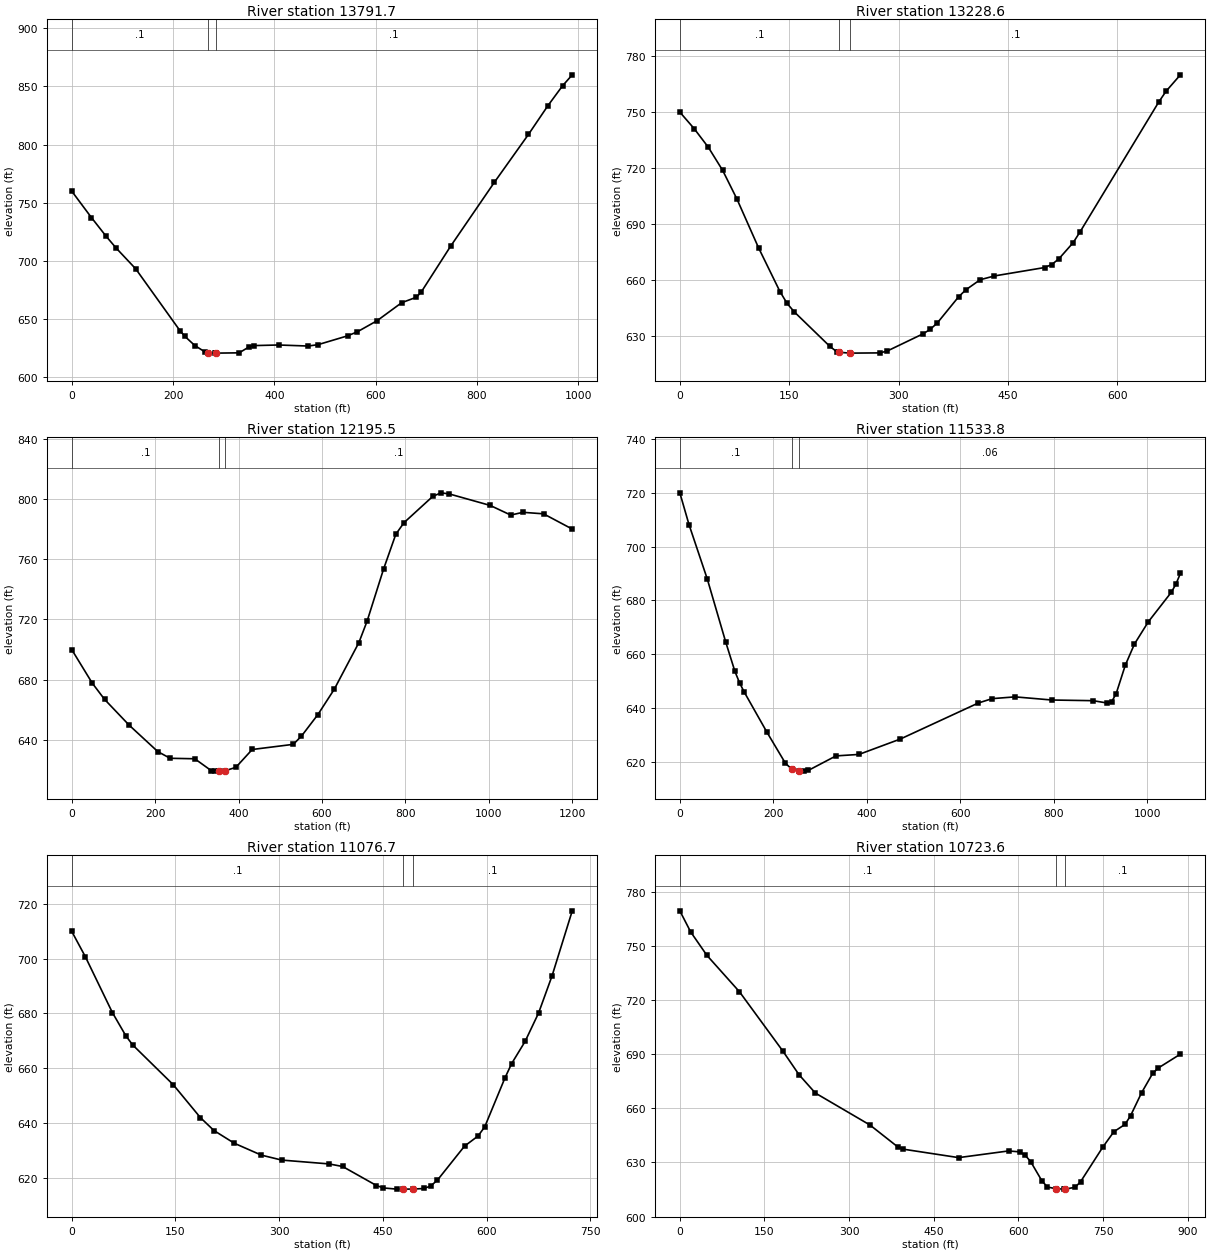
Type RM Length L Ch R = 1 ,13791.7 ,560.4,563.1,565.8
XS GIS Cut Line= 3
     1511350.763      321675.982     1512049.716      321712.345
     1512325.949      321794.092
#Sta/Elev= 30
       0     760    38.9  737.24      68   721.1    87.5   711.1   126.4  693.08
   213.9  639.81   223.6  634.94     243  627.14   262.5  621.78   268.9  621.07
   281.9   620.6   283.9   620.6   330.5  620.85     350  625.94   359.7  627.08
   408.3   627.6   466.6   626.7     486  627.86   544.4  635.45   563.8  638.94
   602.7  648.46   651.3  663.98   680.5   668.7   690.2  673.35   747.9  712.56
   834.3  767.56   901.6  808.77     940  833.49   968.8  850.54     988     860
#Mann= 3 , 0 , 0
       0      .1       0   268.9    .045       0   283.9      .1       0
Bank Sta=268.9,283.9
XS Rating Curve= 0 ,0
Exp/Cntr=0.3,0.1

Type RM Length L Ch R = 1 ,13228.6 ,1029,1033.1,1037.2
XS GIS Cut Line= 2
     1511398.857      322209.231     1512076.236      322319.879
#Sta/Elev= 30
       0  749.98    19.6  741.14    39.2  731.04    58.8  718.65    78.4  703.25
   107.9  677.19   137.3  653.65   147.1  647.28   156.9  642.76   205.9  624.16
   215.7  621.22   218.8  621.03   233.8   620.6   274.5  620.73   284.4  621.73
   333.4  630.94   343.2  633.31     353  636.77   382.4  650.89   392.2  654.58
   411.8  659.99   431.4  662.04   500.1  666.54   509.9  668.13   519.7  671.19
   539.3  679.87   549.1  685.87   656.9  755.52   666.8  761.21   686.4     770
#Mann= 3 , 0 , 0
       0      .1       0   218.8    .045       0   233.8      .1       0
Bank Sta=218.8,233.8
XS Rating Curve= 0 ,0
Exp/Cntr=0.3,0.1

Type RM Length L Ch R = 1 ,12195.5 ,655,661.7,667.9
XS GIS Cut Line= 2
     1510819.878      322939.304     1511919.634      323418.982
#Sta/Elev= 30
       0     700    49.2   677.7    78.7   666.9   137.7  649.75   206.5  632.16
     236  627.74     295  627.42   334.4  619.56   344.2  619.21   353.3  619.28
   368.3  619.53   393.4   621.7   432.7  633.58   531.1     637   550.7  642.46
   590.1  656.77   629.4  673.62   688.4  704.61   708.1  718.87   747.4  753.32
   776.9  776.56   796.6  784.28   865.4   801.7   885.1  804.08   904.8  803.36
  1003.1  795.71  1052.3  789.31  1081.8  791.13    1131  790.13  1199.8     780
#Mann= 3 , 0 , 0
       0      .1       0   353.3    .045       0   368.3      .1       0
Bank Sta=353.3,368.3
XS Rating Curve= 0 ,0
Exp/Cntr=0.3,0.1

Type RM Length L Ch R = 1 ,11533.8 ,434.6,457.1,479.6
XS GIS Cut Line= 2
     1510553.529      323420.985     1511387.261        324092.3
#Sta/Elev= 30
       0  719.99    19.6  708.19    58.9  687.84    98.2  664.47   117.8  653.59
   127.7  649.36   137.5  645.98   186.6  630.89   225.9  619.42     239  617.33
   255.3  616.63   265.2  616.52     275  616.81   333.9  622.18     383  622.73
   471.4  628.44   638.3  641.85   667.8  643.47   716.9  644.13   795.4  642.96
   883.8  642.71   913.3  641.86   923.1  642.24   932.9  645.25   952.6   655.9
   972.2  663.78  1001.7  672.01  1050.8  682.97  1060.6  685.96  1070.4     690
#Mann= 3 , 0 , 0
       0      .1       0     239    .045       0   255.3     .06       0
Bank Sta=239,255.3
XS Rating Curve= 0 ,0
Exp/Cntr=0.3,0.1

Type RM Length L Ch R = 1 ,11076.7 ,355,353.1,351.2
XS GIS Cut Line= 3
     1510467.553      323433.434     1510445.567       323991.36
     1510402.165      324151.083
#Sta/Elev= 30
       0     710    19.6   700.8    58.8  680.36    78.4  671.82    88.2  668.53
   146.9     654   186.1  642.01   205.7  637.29   235.1  632.65   274.3  628.31
   303.7   626.5   372.2   625.1   391.8  624.16   440.8  617.21   450.6  616.34
   470.2   615.9     479   615.9     494  615.92   509.4  616.13   519.2  617.04
     529  619.21   568.1  631.59   587.6  635.27   597.3  638.61   626.5  656.44
   636.2   661.7   655.7   669.8   675.2  680.17   694.7  693.74   723.9  717.47
#Mann= 3 , 0 , 0
       0      .1       0     479    .045       0     494      .1       0
Bank Sta=479,494
XS Rating Curve= 0 ,0
Exp/Cntr=0.3,0.1

Type RM Length L Ch R = 1 ,10723.6 ,550.1,524.6,499
XS GIS Cut Line= 3
     1510074.995      323202.126     1510109.717      323507.682
     1510106.698      324087.395
#Sta/Elev= 30
       0  769.37    19.2  757.69      48   744.7   105.7  724.54   182.6   691.7
   211.4  678.54   240.2  668.45     337  650.74   386.1  638.66     396  637.36
   494.2  632.68   582.6  636.38   602.3  635.87   612.1  634.04     622  630.37
   641.6   619.9   651.4  616.42     667  615.42   680.9  615.23     682  615.23
   700.6  616.23   710.4  619.39   749.7  638.51   769.3  647.03     789  651.07
   798.8  655.82   818.5  668.66   838.1  679.33   847.9   682.3   887.2     690
#Mann= 3 , 0 , 0
       0      .1       0     667    .045       0     682      .1       0
Bank Sta=667,682
XS Rating Curve= 0 ,0
Exp/Cntr=0.3,0.1

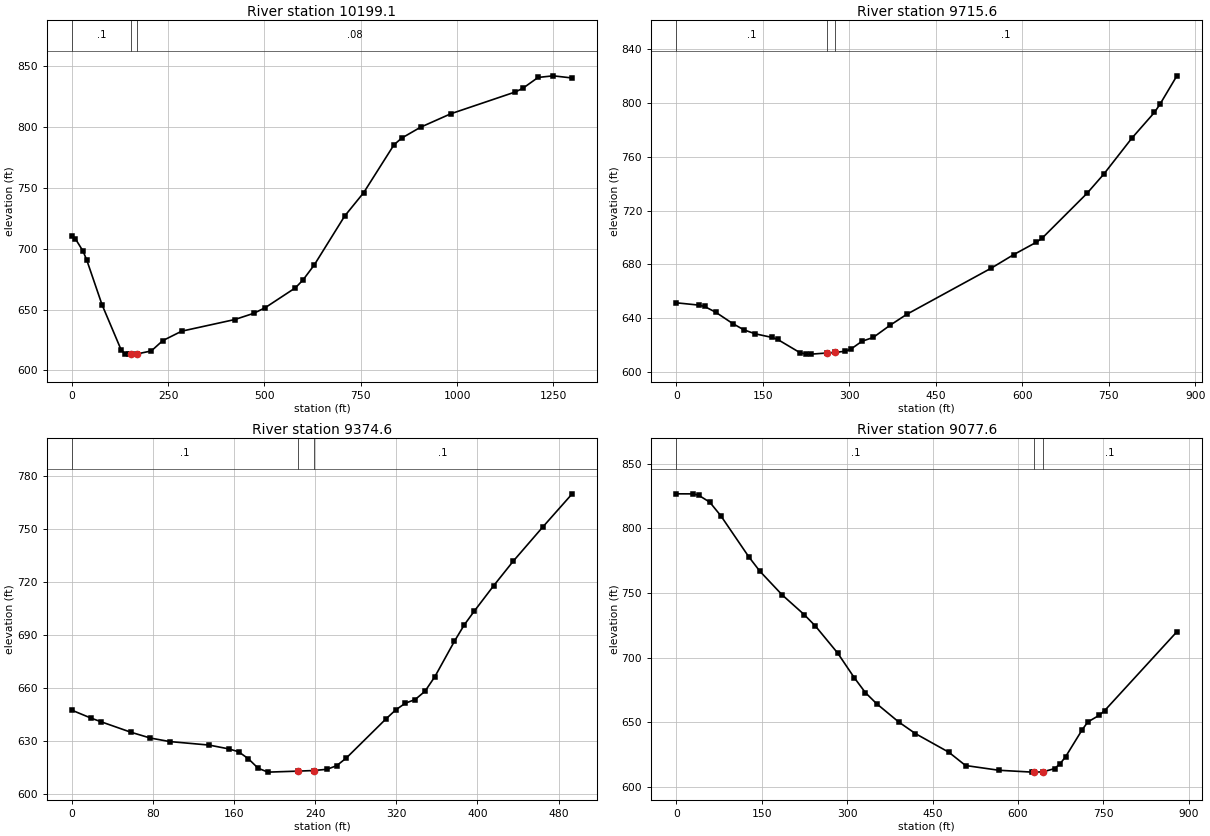
Type RM Length L Ch R = 1 ,10199.1 ,457.4,483.5,509.4
XS GIS Cut Line= 2
     1509472.012      323953.638     1510629.389      324542.438
#Sta/Elev= 30
       0  709.98     9.8  707.95    29.5  697.89    39.4  690.34    78.7  653.99
   127.9   617.2   137.7  613.81   147.6  613.43   154.5  613.44   169.5  613.58
   206.6  616.05   236.1  624.47   285.3  632.25     423   641.8   472.2   646.9
   501.7  651.46   580.4  667.82   600.1  674.25   629.6  686.72   708.3  726.74
   757.5  745.89   836.2   785.2   855.9  790.62     905  799.59   983.7  810.66
    1151  828.54  1170.6  831.56    1210  840.46  1249.4  841.78  1298.5     840
#Mann= 3 , 0 , 0
       0      .1       0   154.5    .045       0   169.5     .08       0
Bank Sta=154.5,169.5
XS Rating Curve= 0 ,0
Exp/Cntr=0.3,0.1

Type RM Length L Ch R = 1 ,9715.6  ,317.9,341,364
XS GIS Cut Line= 2
       1509349.3      324139.626     1509369.549      325007.688
#Sta/Elev= 30
       0  651.48      39  649.77    48.8  648.76    68.3  644.47    97.6  636.11
   117.1   631.4   136.6  628.47   165.8  625.79   175.6   624.3   214.6   614.4
   224.4  613.44   234.2  613.38   260.9  614.21   275.9  614.71   292.7   615.5
   302.4  617.01     322  622.94   341.5  625.77   370.7  634.81     400  643.02
   546.3  677.23   585.4  687.31   624.4  696.43   634.2  699.34   712.2  732.67
   741.5  747.02   790.2  773.74   829.3   792.8     839  798.92   868.3     820
#Mann= 3 , 0 , 0
       0      .1       0   260.9    .045       0   275.9      .1       0
Bank Sta=260.9,275.9
XS Rating Curve= 0 ,0
Exp/Cntr=0.3,0.1

Type RM Length L Ch R = 1 ,9374.6  ,298.6,297,295.1
XS GIS Cut Line= 2
     1509318.484      324059.939     1508907.817      324333.457
#Sta/Elev= 30
       0  647.48    19.4  642.88      29  640.88      58  635.03    77.4  631.68
    96.8  629.66   135.4  627.69   154.8  625.53   164.5  623.92   174.2  619.92
   183.8  614.56   193.5  612.36   223.5  612.93   238.5  613.27   251.6  613.95
   261.2  615.99   270.9  620.44   309.6  642.38   319.3  647.54   328.9   651.4
   338.6  653.48   348.3  658.16     358  666.39   377.3  686.46     387  695.75
   396.7  703.41     416  717.96   435.4  731.92   464.4  751.19   493.4     770
#Mann= 3 , 0 , 0
       0      .1       0   223.5    .045       0   238.5      .1       0
Bank Sta=223.5,238.5
XS Rating Curve= 0 ,0
Exp/Cntr=0.3,0.1

Type RM Length L Ch R = 1 ,9077.6  ,9087.701,9077.7,9067.8
XS GIS Cut Line= 2
     1509453.467       323566.71     1508763.627      324111.394
#Sta/Elev= 30
       0  826.81    29.3  826.77    39.1  825.71    58.6  820.34    78.1  809.77
     127  778.12   146.5  766.92   185.6   748.6   224.6  733.21   244.2  724.39
   283.2  703.53   312.5  684.35     332  672.83   351.6  664.31   390.6  650.08
   419.9  641.11   478.5   626.7   507.8  616.42   566.4  612.74     625   611.3
   628.6   611.3   643.6   611.5   664.1  614.02   673.9  617.79   683.6  623.26
   712.9  644.27   722.7  650.19   742.2  655.22     752  658.88     879     720
#Mann= 3 , 0 , 0
       0      .1       0   628.6    .045       0   643.6      .1       0
Bank Sta=628.6,643.6
XS Rating Curve= 0 ,0
Exp/Cntr=0.3,0.1

Chan Stop Cuts=-1
Use User Specified Reach Order=0
Composite Channel Slope=5